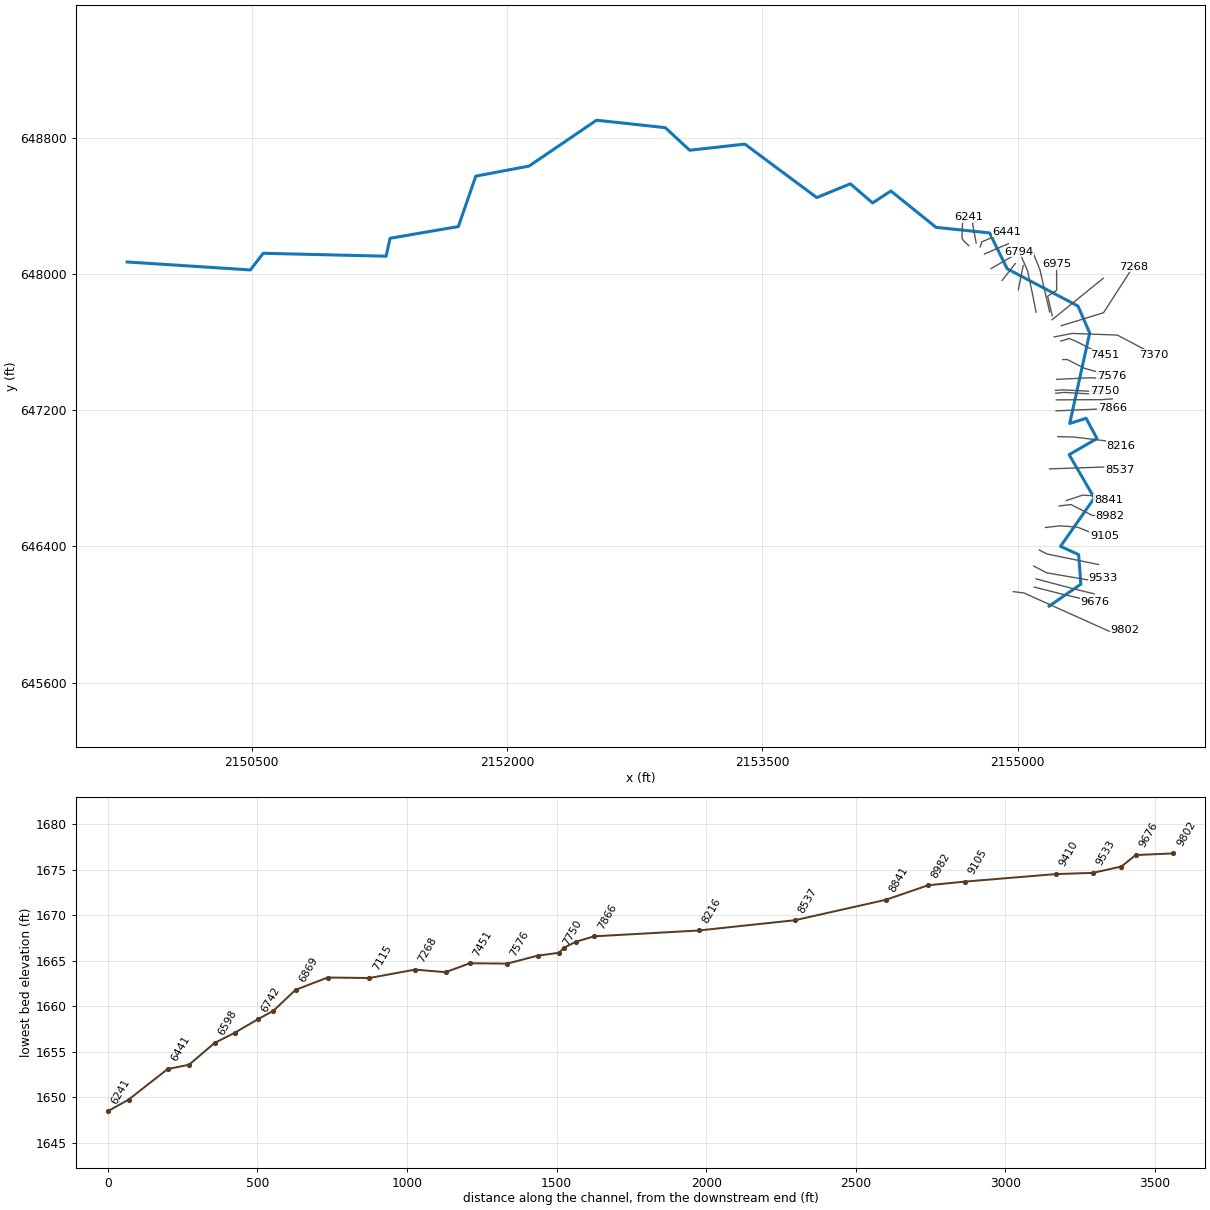
--- LYNNCMPRN.prj (project) ---

Proj Title=LYNNCMPRN
Current Plan=p01
Default Exp/Contr=0,0
English Units
Geom File=g01
Flow File=f01
Plan File=p01
BEGIN DESCRIPTION:
---------- MODELED AS PART OF WVEMD CTP PROGRAM, 2023----------
Stream Name: Lynn Camp Run
Flood Zone:  AFH
Upshur County, WV
HEC-RAS Version: RAS 6.3
Vertical Datum: NAVD88
Projection: NAD 1983 StatePlane West Virginia S FIPS 4702 (US Feet)
Terrain: 1-meter LIDAR (FEMA Region III 3DEP collected 2016-2018)
Land Use: 2019 NLCD
Hydrologic Method:
WV SIR2010-5033 regression equations
Additional Model Notes:
None
END DESCRIPTION:
DSS Export Rating Curves= 0
DSS Export Rating Curve Sorted= 0
DSS Export Volume Flow Curves= 0
DXF OffsetX= 0
DXF OffsetY= 0
DXF ScaleX= 0
DXF ScaleY= 0

--- LYNNCMPRN.p01 (plan) ---

Plan Title=Floodplain
Program Version=6.30
Short Identifier=Floodplain
Geom File=g01
Flow File=f01
Subcritical Flow
K Sum by GR= 0
Std Step Tol= 0.01
Critical Tol= 0.01
Num of Std Step Trials= 20
Max Error Tol= 0.3
Flow Tol Ratio= 0.001
Split Flow NTrial= 30
Split Flow Tol= 0.02
Split Flow Ratio= 0.02
Log Output Level= 0
Friction Slope Method= 1
Unsteady Friction Slope Method= 2
Unsteady Bridges Friction Slope Method= 1
Parabolic Critical Depth
Global Vel Dist= 0 , 0 , 0
Global Log Level= 0
CheckData=False
Encroach Param=-1 ,0,0, 0
Mapping Interval=1HOUR
Computation Time Step Use Courant=        0
Computation Time Step Use Time Series=    0
Computation Time Step Count To Double=0
Computation Time Step Max Doubling=0
Computation Time Step Max Halving=0
Computation Time Step Residence Courant=0
Run HTab= 0
Run UNet= 0
Run Sediment= 0
Run PostProcess= 0
Run WQNet= 0
Run RASMapper=-1
UNET Theta= 0
UNET Theta Warmup= 0
UNET ZTol= 0
UNET ZSATol= 0
UNET MxIter= 0
UNET Max Iter WO Improvement= 0
UNET MaxInSteps= 0
UNET DtIC= 0
UNET DtMin= 0
UNET MaxCRTS= 0
UNET WFStab= 0
UNET SFStab= 0
UNET WFX= 1
UNET SFX= 1
UNET Gravity=32.17405
UNET 1D Methodology=Finite Difference
UNET DSS MLevel= 1
UNET Pardiso=0
UNET DZMax Abort= 0
UNET Use Existing IB Tables= 0
UNET Froude Reduction=False
UNET Froude Limit= 0
UNET Froude Power= 0
UNET D1 Cores= 0
UNET WindReference=Eulerian
UNET WindDragFormulation=Hsu (1988)
UNET D2 Coriolis=0
UNET D2 Cores= 0
UNET D2 Theta= 1
UNET D2 Theta Warmup= 1
UNET D2 Z Tol= 0.01
UNET D2 Volume Tol= 0.01
UNET D2 Max Iterations= 20
UNET D2 Equation= 0
UNET D2 RampUpFraction=0.1
UNET D2 TimeSlices= 1
UNET D2 Turbulence Formulation=Non-Conservative (original)
UNET D2 Eddy Viscosity=0.3
UNET D2 Transverse Eddy Viscosity=0.1
UNET D2 Smagorinsky Mixing=0
UNET D2 BCVolumeCheck=0
UNET D2 Cores=0
UNET D2 SolverType=PARDISO (Direct)
UNET D2 Minimum Iterations= 3
UNET D2 Maximum Iterations= 30
UNET D2 Restart Number= 10
UNET D2 Relaxation Coeff=1.3
UNET D2 SOR Precondition Iterations= 10
UNET D2 ILUT Maximum Fill= 8
UNET D2 ILUT Tolerance=1E-08
UNET D2 Convergence Tolerance=0.00001
UNET D1D2 MaxIter= 0
UNET D1D2 ZTol=0.01
UNET D1D2 QTol=0.1
UNET D1D2 MinQTol=1
Write IC File= 0
Write IC File at Fixed DateTime=0
Write IC File at Sim End=0
Echo Input=False
Echo Parameters=False
Echo Output=False
Write Detailed= 0
HDF Write Warmup=0
HDF Write Time Slices=0
HDF Flush=0
HDF Compression= 1
HDF Chunk Size= 1
HDF Spatial Parts= 1
HDF Use Max Rows=0
HDF Fixed Rows= 1
Calibration Method= 0
Calibration Iterations= 20
Calibration Max Change=0.05
Calibration Tolerance=0.2
Calibration Maximum=1.5
Calibration Minimum=0.5
Calibration Optimization Method= 1
WQ AD Non Conservative
WQ ULTIMATE=-1
WQ Max Comp Step=1HOUR
WQ Output Interval=15MIN
WQ Output Selected Increments= 0
WQ Output face flow=0
WQ Output face velocity=0
WQ Output face area=0
WQ Output face dispersion=0
WQ Output cell volume=0
WQ Output cell surface area=0
WQ Output cell continuity=0
WQ Output cumulative cell continuity=0
WQ Output face conc=0
WQ Output face dconc_dx=0
WQ Output face courant=0
WQ Output face peclet=0
WQ Output face adv mass=0
WQ Output face disp mass=0
WQ Output cell mass=0
WQ Output cell source sink temp=0
WQ Output nsm pathways=0
WQ Output nsm derived pathways=0
WQ Create Restart=0
WQ Fixed Restart=0
WQ System Summary=0
WQ Write To DSS=0
Sorting and Armoring Iterations= 10
XS Update Threshold= 0.02
Bed Roughness Predictor= 0
Hydraulics Update Threshold= 0.02
Energy Slope Method= 1
Volume Change Method= 1
Sediment Retention Method= 0
Sediment TS Multiplier= 1
Warm Up Method= 0
XS Weighting Method= 0
Number of US Weighted Cross Sections= 1
Number of DS Weighted Cross Sections= 1
Upstream XS Weight=0
Main XS Weight=1
Downstream XS Weight=0
Number of DS XS's Weighted with US Boundary= 1
Upstream Boundary Weight= 1
Weight of XSs Associated with US Boundary= 0
Number of US XS's Weighted with DS Boundary= 1
Downstream Boundary Weight= 0.5
Weight of XSs Associated with DS Boundary= 0.5
Percentile Method= 0
Sediment Output Level= 3
Mass or Volume Output= 0
Output Increment Type= 1
Profile and TS Output Increment= 1
Transport Output Increment 1
XS Output Flag= 0
XS Output Increment= 10
Read HDF5 Sediment Hotstart= 0
Sediment Hotstart Type= 0
Write Gradation File= 0
Read Gradation Hotstart= 0
Write HDF5 File= 1
Write Binary Output= 1
Write DSS Sediment File= 0
DSS Sediment Output Type= 1
SV Curve= 0
Specific Gage Flag= 0
Subcell Erosion Methods= 0
Subcell Deposition Methods= 0
Advection Scheme= 1
Matrix Solver= 0
Implicit Weighting Factor= 1
Maximum Outer Loop Convergence Iterations= 5
Convergence Maximum Absolute= 0.001
Convergence RMSE= 0.0001
Grain Fractions Max Abs Error= 0.001
Max Subgrid Regions= 1
Max Subgrid Length Scale= 3.402823E+38
Initial Layer Thickness= 3.402823E+38
Min Layer Thickness= 3.402823E+38
Max Layer Thickness= 3.402823E+38
Number of Layers= 5

--- LYNNCMPRN.f01 (steady flow) ---

Flow Title=Flows
Program Version=6.30
Number of Profiles= 1
Profile Names=01pct
River Rch & RM=LYNNCMPRN,Main,9802
     757
River Rch & RM=LYNNCMPRN,Main,6513
     846
River Rch & RM=LYNNCMPRN,Main,3563
     973
Boundary for River Rch & Prof#=LYNNCMPRN,Main            , 1
Up Type= 0
Dn Type= 3
Dn Slope=0.05
DSS Import GetInterval= 0
DSS Import GetPeak= 0
DSS Import FillOption= 0

--- LYNNCMPRN.g01 (geometry) ---

Geom Title=Geometry
Program Version=6.31

River Reach=LYNNCMPRN       ,Main
Reach XY= 30
2155186.03200436646049.653603428     2155372.164646178.549999997
2155359.11500004646351.9360000192155252.83300003646401.042000011
     2155451.174646684.9169999962155303.31300001646939.288000017
2155466.82700002647034.352000013     2155402.984647153.194999993
2155306.74700002647122.7479999962155423.93100002 647654.32600002
2155355.36600001 647812.488000022154938.79700002648031.890000016
2154835.86400002648242.4210000192154521.28400002648275.015000001
2154255.83800003648488.694000021     2154148.413648418.498000011
2154017.60700002648530.9030000122153820.15400001648450.003999993
2153397.66200002648764.1260000022153073.29500003648728.156000018
2152930.04100002 648860.821000012152526.09200002648904.547000021
2152130.04100002      648635.3532151816.74899998648575.945000008
2151714.23555178 648279.87816744     2151312.958648210.914000005
2151289.72100002648105.635000005     2150567.558648122.746999994
     2150492.097648024.7930000132149767.99013995648071.660486878

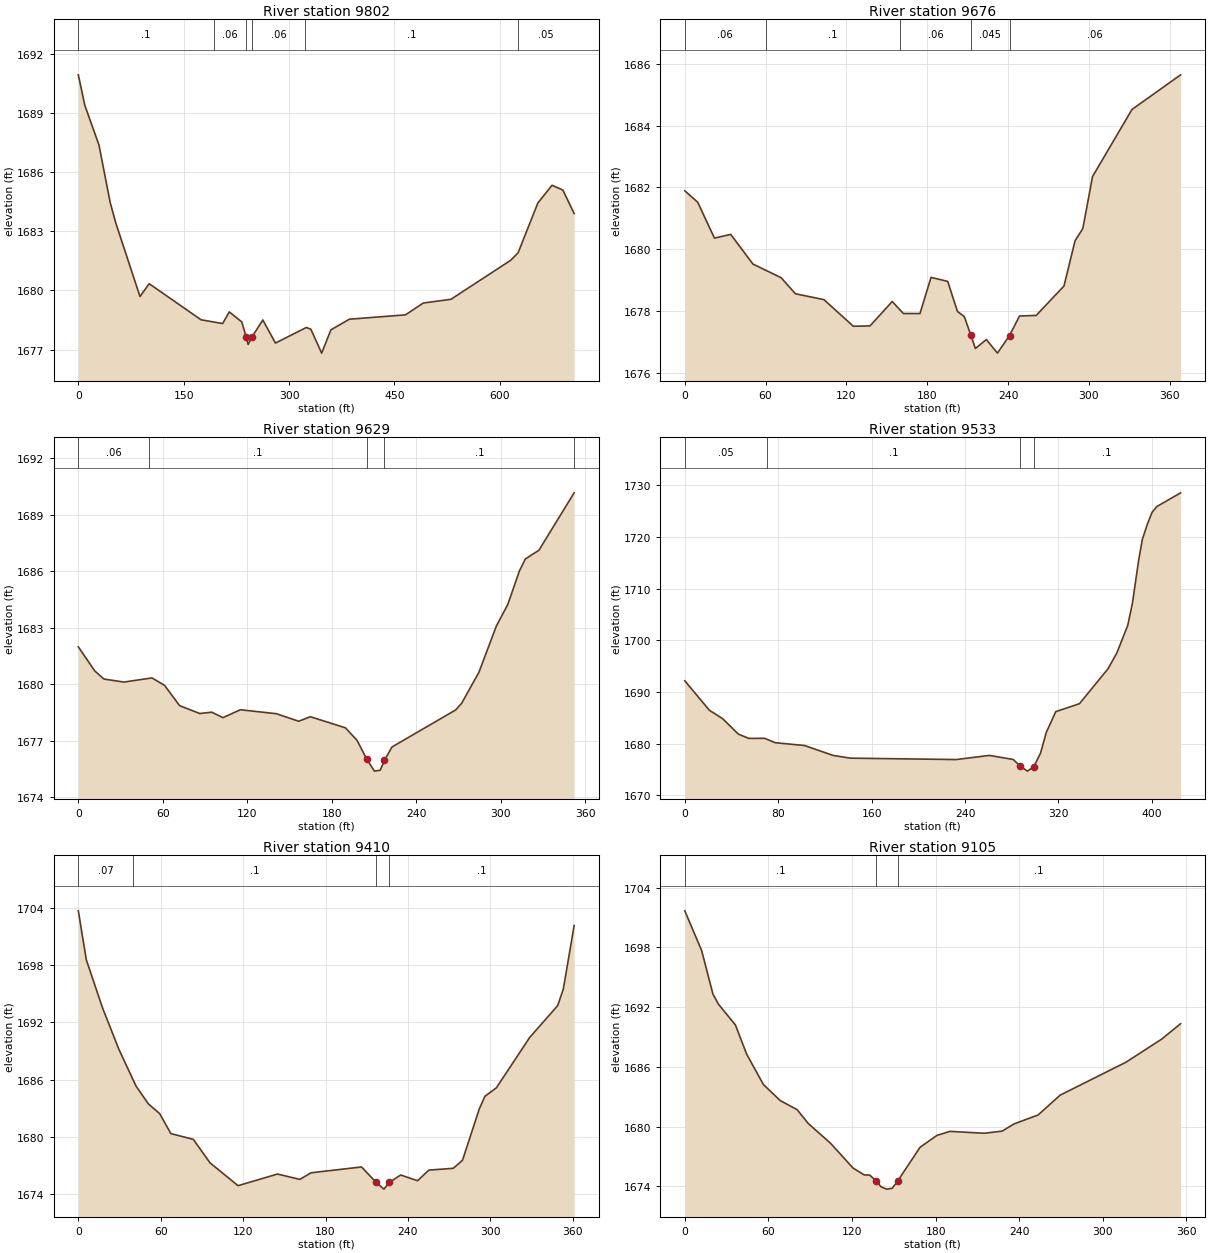
Type RM Length L Ch R = 1 ,9802    ,114.2,126.2,114.2
XS GIS Cut Line= 4
2154975.03145221646134.6844578962155037.58715691 646126.94560783
2155541.90221952645900.5842434132155631.54389944645910.257805994
#Sta/Elev= 30
       0 1690.93     9.2 1689.39    29.4 1687.37    45.4 1684.45    53.5  1683.4
    87.8 1679.69   100.9 1680.34   174.8 1678.51   205.5 1678.32   214.9 1678.91
   232.8  1678.4   238.8 1677.66   241.8 1677.26   247.6 1677.66   262.7  1678.5
   280.7 1677.33   324.6 1678.12   331.1 1678.03   346.5 1676.82   359.6    1678
   385.9 1678.54   465.8 1678.76   491.2 1679.36   530.6 1679.55   615.8 1681.53
   626.2 1681.91   654.3 1684.43   674.4 1685.33   689.9 1685.09     706  1683.9
#Mann= 6 ,-1,0
       0      .1       0  193.03     .06       0   238.8    .045       0
   247.6     .06       0  323.03      .1       0  625.82     .05       0
Bank Sta=238.8,247.6
XS Rating Curve= 0 ,0
Exp/Cntr(USF)=0,0
Exp/Cntr=0.3,0.1

Type RM Length L Ch R = 1 ,9676    ,49,47.6,51.1
XS GIS Cut Line= 4
2155098.87097599646161.365689381  2155262.087464646119.964433887
2155351.25939891646099.2638061412155456.35489362646073.786110452
#Sta/Elev= 30
       0 1681.89     9.6 1681.52      22 1680.36    34.1 1680.48    50.6 1679.52
    71.5 1679.08    82.1 1678.56   103.3 1678.37   125.1 1677.51   137.5 1677.52
     154 1678.31   162.3 1677.92   174.6 1677.92   182.8 1679.09   195.2 1678.96
   202.4 1677.99   207.5 1677.82   212.4 1677.22   215.7 1676.79   223.9 1677.08
   232.1 1676.64  241.07 1677.21   248.5 1677.84   260.9 1677.86   281.5 1678.81
   289.7 1680.27   295.5 1680.67   302.7 1682.35     332 1684.52   368.1 1685.64
#Mann= 5 ,-1,0
       0     .06       0      60      .1       0     160     .06       0
   212.4    .045       0  241.07     .06       0
Bank Sta=212.4,241.07
XS Rating Curve= 0 ,0
Exp/Cntr(USF)=0,0
Exp/Cntr=0.3,0.1

Type RM Length L Ch R = 1 ,9629    ,94.3,95.4,94.4
XS GIS Cut Line= 3
2155108.87296606646209.8275115612155311.73672698646156.109677159
2155449.81909645646121.808314993
#Sta/Elev= 30
       0 1681.98    11.7  1680.7    18.2 1680.27    32.4 1680.11    52.3 1680.33
    61.3 1679.93    71.9 1678.86    86.2 1678.44    94.8 1678.51   102.7 1678.22
   115.1 1678.64   140.6 1678.43   156.5 1678.03   164.8 1678.27   189.7 1677.68
   197.9 1677.02   204.91676.005   210.3 1675.38   214.4 1675.43   217.4 1675.95
   222.7 1676.66     268 1678.63   272.2 1678.98   284.5 1680.63   296.9 1683.09
     305 1684.23   313.3 1686.02   317.5 1686.65   327.1 1687.11   352.1 1690.16
#Mann= 5 ,-1,0
       0     .06       0      50      .1       0   204.9    .045       0
   217.4      .1       0  352.13     .06       0
Bank Sta=204.9,217.4
XS Rating Curve= 0 ,0
Exp/Cntr(USF)=0,0
Exp/Cntr=0.3,0.1

Type RM Length L Ch R = 1 ,9533    ,122.7,123,123.3
XS GIS Cut Line= 4
2155095.43347421646284.7790047772155171.38885448646245.368194258
2155450.13076888646197.3586614442155503.17489881646215.877171743
#Sta/Elev= 30
       0 1692.15      21 1686.47    32.4 1684.83    45.9 1681.84    54.9 1681.01
    68.4 1681.03    77.4 1680.18   102.6 1679.63     127 1677.72   141.8 1677.19
   232.5 1676.92   260.9 1677.72   281.2 1676.94   287.2 1675.67   293.4 1674.68
   298.8 1675.53   304.6 1678.14   309.6 1682.19   317.7 1686.19     338 1687.73
   362.4 1694.48   369.9  1697.5   379.3 1702.85   383.3 1707.12   388.7 1715.54
   391.8 1719.49     396 1722.39   400.2 1724.77   404.4 1725.89   424.6 1728.52
#Mann= 4 ,-1,0
       0     .05       0      70      .1       0   287.2    .045       0
   298.8      .1       0
Bank Sta=287.2,298.8
XS Rating Curve= 0 ,0
Exp/Cntr(USF)=0,0
Exp/Cntr=0.3,0.1

Type RM Length L Ch R = 1 ,9410    ,296.8,305.5,300.3
XS GIS Cut Line= 4
2155126.93872844646379.7162667082155172.15377481646356.125807734
2155441.47818144 646301.081403462155475.88093411646294.200852926
#Sta/Elev= 30
       0 1703.68     5.8 1698.56    17.6 1693.53    29.5 1689.19      42 1685.34
      51 1683.47    59.2 1682.46    67.4 1680.36    83.7 1679.76    95.9  1677.3
   116.3 1674.91     145 1676.13   161.3 1675.57   169.4 1676.26   206.2 1676.87
   216.51675.305   222.5 1674.55   226.4 1675.25   234.7 1676.03     247 1675.43
   255.2 1676.54     273 1676.73   279.7 1677.57   291.9 1682.93     296 1684.26
   304.4 1685.16   328.6 1690.42     349 1693.76   353.1 1695.49     361 1702.14
#Mann= 4 ,-1,0
       0     .07       0      40      .1       0   216.5    .045       0
   226.4      .1       0
Bank Sta=216.5,226.4
XS Rating Curve= 0 ,0
Exp/Cntr(USF)=0,0
Exp/Cntr=0.3,0.1

Type RM Length L Ch R = 1 ,9105    ,127.6,122.1,117.9
XS GIS Cut Line= 5
2155164.13228359646511.5323239472155249.64769738646521.361681853
2155352.00971213 646513.758536582155447.21207829646475.677590115
 2155510.6803224646463.830184549
#Sta/Elev= 30
       0 1701.66    12.1 1697.67    20.2  1693.3    24.2 1692.28    36.3 1690.21
    44.3  1687.3    56.4 1684.22    68.5 1682.61    80.6  1681.7    88.6 1680.31
   104.7 1678.31   120.7 1675.84   128.7 1675.15   132.7 1675.13   137.21674.557
   140.8 1673.96   144.8 1673.72   148.8  1673.8   152.8 1674.54   168.8 1677.92
   180.9 1679.11   190.3 1679.52   214.7 1679.33   227.7 1679.54   236.3 1680.27
   253.5 1681.16   269.3 1683.15   316.7 1686.47   342.2 1688.78   355.8 1690.33
#Mann= 3 ,-1,0
       0      .1       0   137.2    .045       0   152.8      .1       0
Bank Sta=137.2,152.8
XS Rating Curve= 0 ,0
Exp/Cntr(USF)=0,0
Exp/Cntr=0.3,0.1

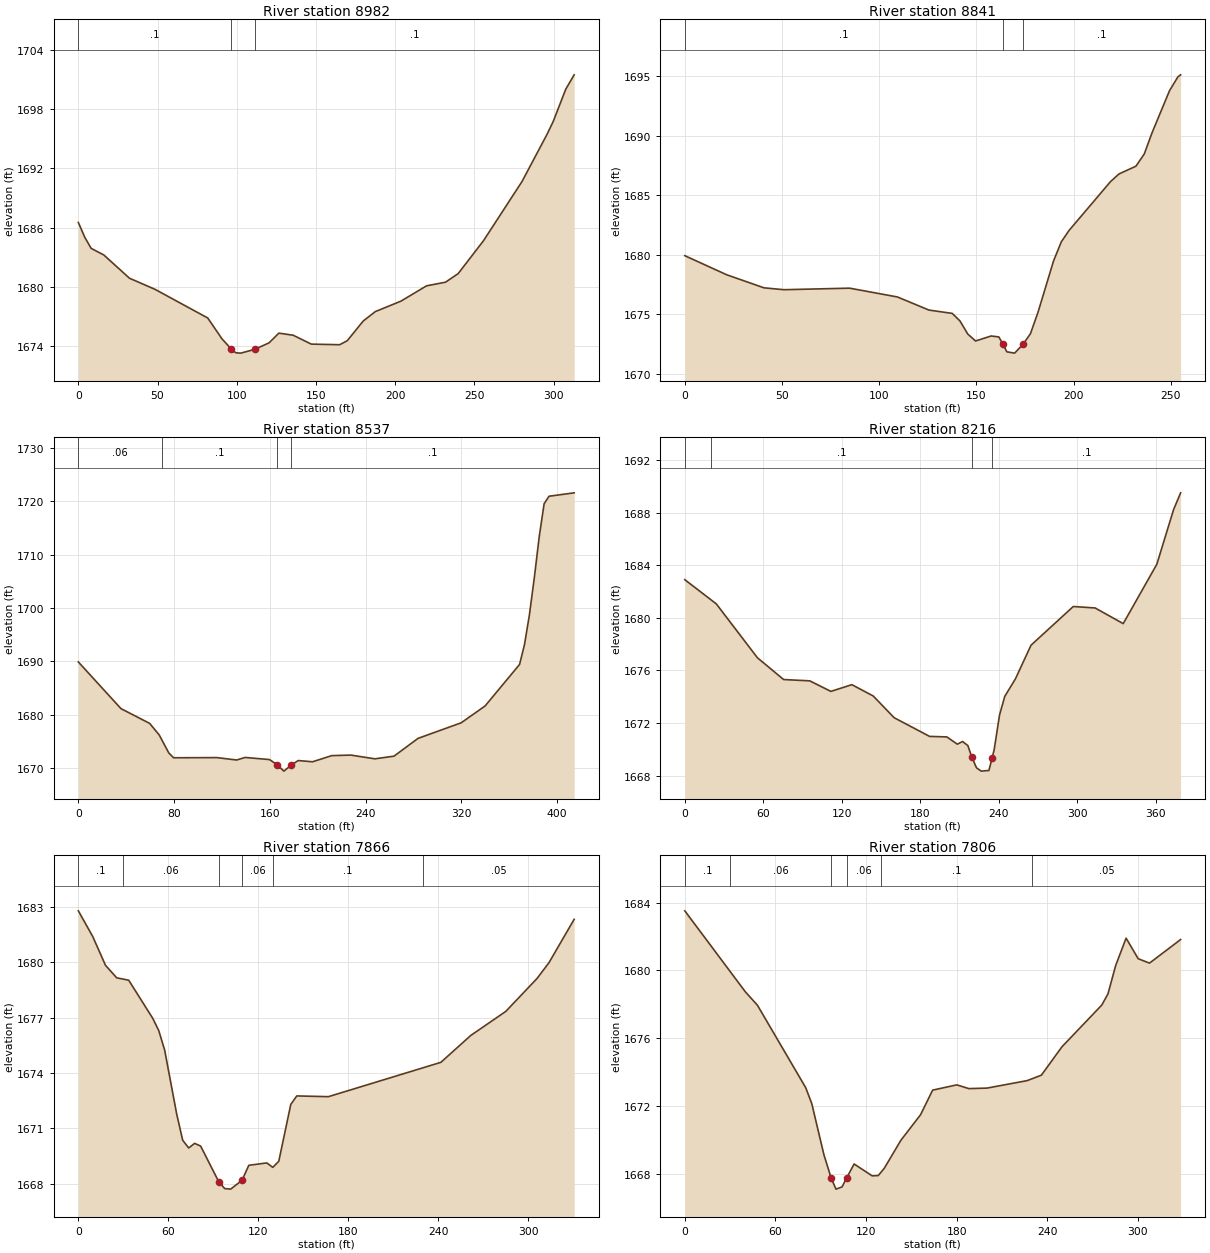
Type RM Length L Ch R = 1 ,8982    ,139.4,141.7,145.6
XS GIS Cut Line= 4
2155244.13659125646638.2479359142155313.95165977646646.287246834
 2155439.6187831646582.3958810992155541.35522425646580.963735641
#Sta/Elev= 30
       0 1686.53     4.1 1685.02     8.1 1683.91    16.1 1683.24    32.3 1680.89
    48.4 1679.77    81.7 1676.87    90.7 1674.76    96.6 1673.73    99.5 1673.35
   102.5 1673.32   111.4  1673.7   120.4 1674.36   126.6 1675.34   135.6 1675.13
   147.1 1674.23     165 1674.17   169.8 1674.58   179.8 1676.56   187.5 1677.52
   203.6 1678.57   219.8 1680.12   231.8 1680.49   239.8 1681.36   255.8 1684.69
   280.1 1690.67   295.8 1695.41   299.8 1696.74   307.7    1700     313 1701.45
#Mann= 3 ,-1,0
       0      .1       0    96.6    .045       0   111.4      .1       0
Bank Sta=96.6,111.4
XS Rating Curve= 0 ,0
Exp/Cntr(USF)=0,0
Exp/Cntr=0.3,0.1

Type RM Length L Ch R = 1 ,8841    ,303.5,303.5,303.5
XS GIS Cut Line= 4
2155287.75493976646670.1228923992155382.55585308646701.723196837
2155483.80580811646695.9190592872155533.46342937646675.282125776
#Sta/Elev= 30
       0 1679.91    21.5 1678.31    40.7 1677.21      51 1677.05    84.8 1677.18
   109.4 1676.44   125.6 1675.34   137.6 1675.06   141.6 1674.42   145.6 1673.32
   149.6 1672.74   157.6 1673.16   161.6 1673.08   163.51672.518   165.7 1671.83
   169.7 1671.72     174 1672.46   177.8 1673.34   181.7 1675.14   189.7 1679.46
   193.7 1681.07   197.7 1682.03     219 1686.13   223.4 1686.78   232.1 1687.43
   236.4 1688.46   240.4 1690.24   249.4 1693.78   253.7 1694.94   255.1 1695.11
#Mann= 3 ,-1,0
       0      .1       0   163.5    .045       0     174      .1       0
Bank Sta=163.5,174
XS Rating Curve= 0 ,0
Exp/Cntr(USF)=0,0
Exp/Cntr=0.3,0.1

Type RM Length L Ch R = 1 ,8537    ,321.4,321.4,321.4
XS GIS Cut Line= 3
2155188.58295355646856.0738368912155527.51592405646867.538799952
2155600.60506357 646850.34135536
#Sta/Elev= 30
       0 1689.91    35.6 1681.18    59.6 1678.41    67.6 1676.24    75.6 1672.87
    79.6 1671.98   115.7 1672.01   132.3 1671.56   139.3 1672.04   159.7 1671.64
   165.91670.714   171.7 1669.48     1781670.631   183.7 1671.46   195.7 1671.23
   211.7 1672.38   227.7 1672.48   247.7 1671.78   263.7 1672.28   283.8 1675.61
   319.8 1678.52   339.8 1681.67   368.6 1689.44   372.7 1693.14   376.8  1698.7
   380.9 1705.62     385 1713.31   389.1  1719.5   393.2 1720.91   414.2 1721.55
#Mann= 4 ,-1,0
       0     .06       0      70      .1       0   165.9    .045       0
     178      .1       0
Bank Sta=165.9,178
XS Rating Curve= 0 ,0
Exp/Cntr(USF)=0,0
Exp/Cntr=0.3,0.1

Type RM Length L Ch R = 1 ,8216    ,342.6,349.4,341.2
XS GIS Cut Line= 4
2155236.59248637647045.2457274052155332.61155201647043.096046831
2155538.26432692647018.0164401342155609.20378586646990.787152863
#Sta/Elev= 30
       0  1682.9    24.1 1681.06    55.6 1676.96    75.6 1675.31    95.6 1675.21
   111.7 1674.41   127.8 1674.92   144.1 1674.06   160.1 1672.41   187.2 1670.99
   200.4 1670.95   208.4  1670.4   212.5  1670.6   216.5 1670.29   219.5 1669.41
   223.1  1668.6   226.7 1668.35   232.6  1668.4   235.11669.376   236.6 1669.98
   240.7 1672.61   244.7 1674.03   252.8 1675.35   264.8 1677.92   297.1 1680.86
   313.8 1680.75   335.3 1679.56     361 1684.07   373.8 1688.22   379.2  1689.5
#Mann= 4 ,-1,0
       0     .06       0      20      .1       0   219.5    .045       0
   235.1      .1       0
Bank Sta=219.5,235.1
XS Rating Curve= 0 ,0
Exp/Cntr(USF)=0,0
Exp/Cntr=0.3,0.1

Type RM Length L Ch R = 1 ,7866    ,61.4,61,60.3
XS GIS Cut Line= 3
2155226.62010524647196.919272798 2155460.9352878647206.951115477
2155556.95435344647212.683597008
#Sta/Elev= 30
       0 1682.79     9.6  1681.4    18.1 1679.84    25.6 1679.16    33.6 1679.03
    49.6 1676.97    53.6 1676.31    57.6 1675.24    65.6 1671.78    69.6 1670.36
    73.6 1669.94    77.6 1670.19    81.6 1670.04    93.6 1668.12    97.6 1667.74
   101.6 1667.71   109.2 1668.19   113.7    1669   125.7 1669.13   129.7 1668.89
   133.7 1669.22   141.7  1672.3   145.7 1672.76   166.8 1672.72   241.8 1674.58
   261.8 1676.04   285.1 1677.34   305.9 1679.12   313.9 1679.98   330.7 1682.33
#Mann= 6 ,-1,0
       0      .1       0      30     .06       0    93.6    .045       0
   109.2     .06       0     130      .1       0     230     .05       0
Bank Sta=93.6,109.2
XS Rating Curve= 0 ,0
Exp/Cntr(USF)=0,0
Exp/Cntr=0.3,0.1

Type RM Length L Ch R = 1 ,7806    ,41.8,40.5,40.6
XS GIS Cut Line= 3
2155228.05322562647261.4096900192155496.04673718647262.842810402
2155556.23779325 647267.14217155
#Sta/Elev= 30
       0 1683.51    40.1 1678.74    48.1 1677.95    80.1 1673.09    84.1 1672.15
    92.1 1669.15    96.9 1667.78   100.1 1667.12   104.1 1667.25   107.3  1667.8
   112.1  1668.6   124.1  1667.9   128.1 1667.92   132.1 1668.35   143.1    1670
   156.1  1671.5   164.1 1672.95   180.1 1673.26   188.1 1673.04   200.1 1673.07
   226.7 1673.51   236.1 1673.83   249.7  1675.5   276.1 1677.96   280.2 1678.62
   285.3 1680.29   292.2  1681.9   300.2 1680.69   307.7 1680.43   328.3 1681.82
#Mann= 6 ,-1,0
       0      .1       0      30     .06       0    96.9    .045       0
   107.3     .06       0     130      .1       0     230     .05       0
Bank Sta=96.9,107.3
XS Rating Curve= 0 ,0
Exp/Cntr(USF)=0,0
Exp/Cntr=0.3,0.1

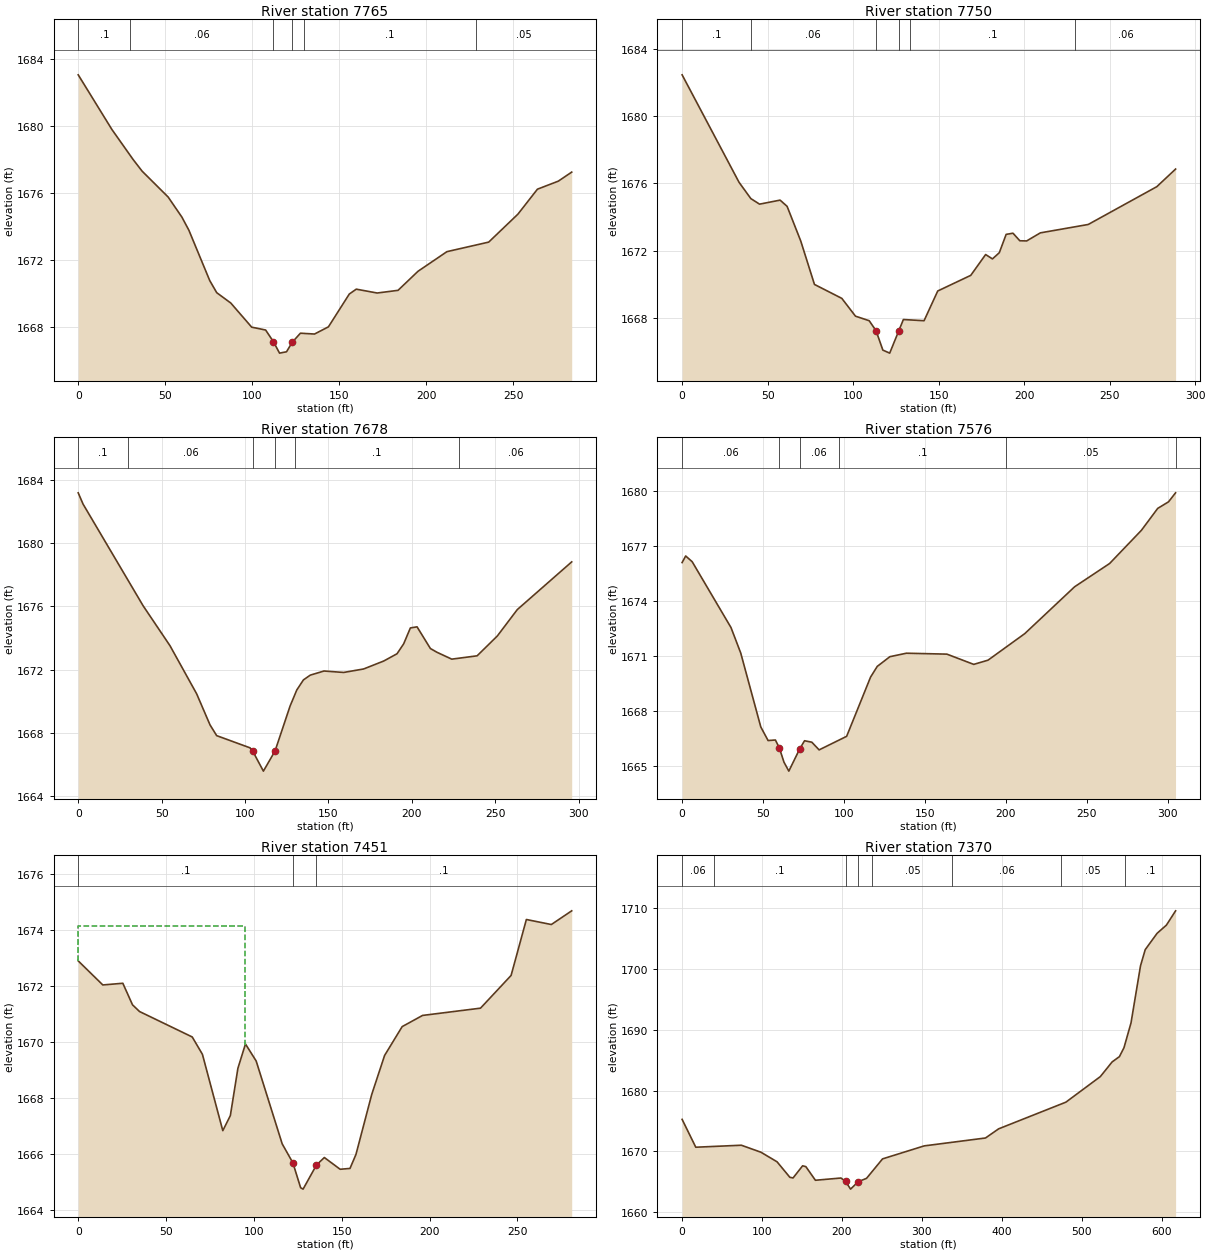
Type RM Length L Ch R = 1 ,7765    ,15.1,15.3,15.2
XS GIS Cut Line= 4
2155224.86375963647300.089145874 2155274.2152234647305.396335058
2155432.61647866  647295.85792962155507.93212832647296.704172855
#Sta/Elev= 30
       0 1683.07    19.4  1679.8    31.5 1678.02    36.7 1677.32    51.7 1675.77
    59.6 1674.57    63.6 1673.79    75.6 1670.78    79.6 1670.06    87.7 1669.44
    99.7    1668   107.7 1667.83   112.2 1667.13   115.7 1666.45   119.7 1666.53
     1231667.099   127.7 1667.64   135.8 1667.59   143.8 1668.02   155.8 1669.98
   159.8 1670.27   171.8 1670.04   183.8  1670.2   195.3 1671.34   211.9 1672.51
   235.9 1673.08   252.7 1674.75   263.9 1676.24   275.9 1676.72   283.6 1677.26
#Mann= 6 ,-1,0
       0      .1       0      30     .06       0   112.2    .045       0
     123     .06       0  129.64      .1       0  228.32     .05       0
Bank Sta=112.2,123
XS Rating Curve= 0 ,0
Exp/Cntr(USF)=0,0
Exp/Cntr=0.3,0.1

Type RM Length L Ch R = 1 ,7750    ,70.7,72,73
XS GIS Cut Line= 4
 2155222.9532343647317.2131395982155265.84557294647320.231448108
2155432.55549411647311.769015561 2155511.2561168647313.038380443
#Sta/Elev= 30
       0 1682.47    33.3 1676.07    40.2  1675.1    45.3 1674.77    57.3 1675.01
    61.4 1674.64    69.4 1672.57    77.4 1669.99    93.4 1669.16   101.4  1668.1
   109.4 1667.83   113.4 1667.24   117.4 1666.08   121.4  1665.9   126.6  1667.2
   129.4  1667.9   141.5 1667.83   149.5  1669.6   168.8 1670.53   177.5 1671.77
   181.5 1671.51   185.5 1671.88   189.5 1672.97   193.5 1673.04   197.5 1672.59
   201.5 1672.58   209.5 1673.06   237.5 1673.56   277.6 1675.81   288.6 1676.86
#Mann= 6 ,-1,0
       0      .1       0      40     .06       0   113.4    .045       0
   126.6     .06       0     133      .1       0  229.92     .06       0
Bank Sta=113.4,126.6
XS Rating Curve= 0 ,0
Exp/Cntr(USF)=0,0
Exp/Cntr=0.3,0.1

Type RM Length L Ch R = 1 ,7678    ,107.4,102.1,95.9
XS GIS Cut Line= 3
2155229.28481698647381.8551896352155427.53313658647391.409325519
2155524.66685141647385.836079587
#Sta/Elev= 30
       0 1683.16     2.9 1682.45    38.9 1676.03      55 1673.51      71 1670.47
      79 1668.51      83 1667.83     103 1667.06   104.71666.831     111 1665.59
     1181666.866     127  1669.7     131 1670.71     135 1671.35   139.1 1671.65
   147.3 1671.91   159.1 1671.82   171.1 1672.04   183.1 1672.54   191.1    1673
   195.1 1673.63   199.1 1674.63   203.1  1674.7   211.1 1673.33   215.1 1673.09
   223.9 1672.66   239.1 1672.87   251.2 1674.12   263.2 1675.79   295.8  1678.8
#Mann= 6 ,-1,0
       0      .1       0      30     .06       0   104.7    .045       0
     118     .06       0     130      .1       0  228.48     .06       0
Bank Sta=104.7,118
XS Rating Curve= 0 ,0
Exp/Cntr(USF)=0,0
Exp/Cntr=0.3,0.1

Type RM Length L Ch R = 1 ,7576    ,124.5,124.9,124.3
XS GIS Cut Line= 5
2155265.95836757647498.422813028 2155292.6574003647498.422813028
2155393.64939367647446.7659888342155488.83724949647420.066956105
2155552.68276253 647404.39578472
#Sta/Elev= 30
       0  1676.1     2.2 1676.46     6.2 1676.15    30.2 1672.55    36.2 1671.16
    48.6 1667.12    53.1 1666.38    57.6 1666.41      60 1665.99    62.9  1665.2
    65.9 1664.71    72.6 1665.92    75.6 1666.37    80.1 1666.29    84.6 1665.87
   101.6 1666.61   116.4 1669.85   120.5 1670.43   128.3 1670.96   138.5 1671.15
   163.5  1671.1   180.1 1670.54   188.9 1670.77   211.6 1672.22   242.4 1674.78
     264 1676.05   283.6 1677.86   293.7 1679.06   300.4 1679.42   304.7 1679.91
#Mann= 6 ,-1,0
       0     .06       0      60    .045       0    72.6     .06       0
    96.7      .1       0  200.14     .05       0  304.74      .1       0
Bank Sta=60,72.6
XS Rating Curve= 0 ,0
Exp/Cntr(USF)=0,0
Exp/Cntr=0.3,0.1

Type RM Length L Ch R = 1 ,7451    ,74.9,81.1,85.1
XS GIS Cut Line= 5
2155254.81900592647606.5403340172155302.87726483647622.211505402
2155348.32366185 647603.406099742155432.42561495647560.049192243
2155511.82621663647525.572615196
#Sta/Elev= 30
       0 1672.91      14 1672.05    25.4 1672.11    30.9 1671.34    34.9  1671.1
    64.9 1670.19    70.7 1669.57    82.3 1666.84    86.6 1667.38    90.9 1669.07
    95.2 1669.94   101.3 1669.33   116.1 1666.37   122.21665.689   126.6  1664.8
     128 1664.75   135.6 1665.61   140.1 1665.88   149.1 1665.46   154.7 1665.49
   158.1 1665.99   167.1 1668.14   174.4 1669.53   184.4 1670.56     196 1670.96
     229 1671.22   246.4 1672.39   255.1 1674.39   269.3 1674.21   280.9  1674.7
#Mann= 3 ,-1,0
       0      .1       0   122.2    .045       0   135.6      .1       0
#XS Ineff= 2 , 0
           94.68 1674.15
Permanent Ineff=
       F       F
Bank Sta=122.2,135.6
XS Rating Curve= 0 ,0
Exp/Cntr(USF)=0,0
Exp/Cntr=0.3,0.1

Type RM Length L Ch R = 1 ,7370    ,96.9,101.7,104.9
XS GIS Cut Line= 4
 2155215.3893713647631.3838076562155321.53286036647651.898935794
2155587.33756405647642.0873527712155802.30042844647527.916204877
#Sta/Elev= 30
       0 1675.26    17.1 1670.67    74.1    1671    98.6 1669.85   118.8 1668.27
   134.8 1665.72   138.8 1665.61   150.8 1667.61   154.8 1667.48   166.8 1665.23
   198.8  1665.6   204.51665.041   210.8 1663.77   220.2 1664.98   230.8 1665.55
   250.8 1668.75   302.9 1670.89   379.6 1672.19   396.1  1673.7   480.2 1678.09
   523.3  1682.3   538.1 1684.72   547.2 1685.59   552.9 1687.06   561.7 1691.14
   573.6 1700.55   579.5 1703.21   594.3 1705.89     606 1707.25   617.5  1709.6
#Mann= 8 ,-1,0
       0     .06       0      40      .1       0   204.5    .045       0
   220.2      .1       0  238.11     .05       0  338.11     .06       0
  474.09     .05       0  554.09      .1       0
Bank Sta=204.5,220.2
XS Rating Curve= 0 ,0
Exp/Cntr(USF)=0,0
Exp/Cntr=0.3,0.1

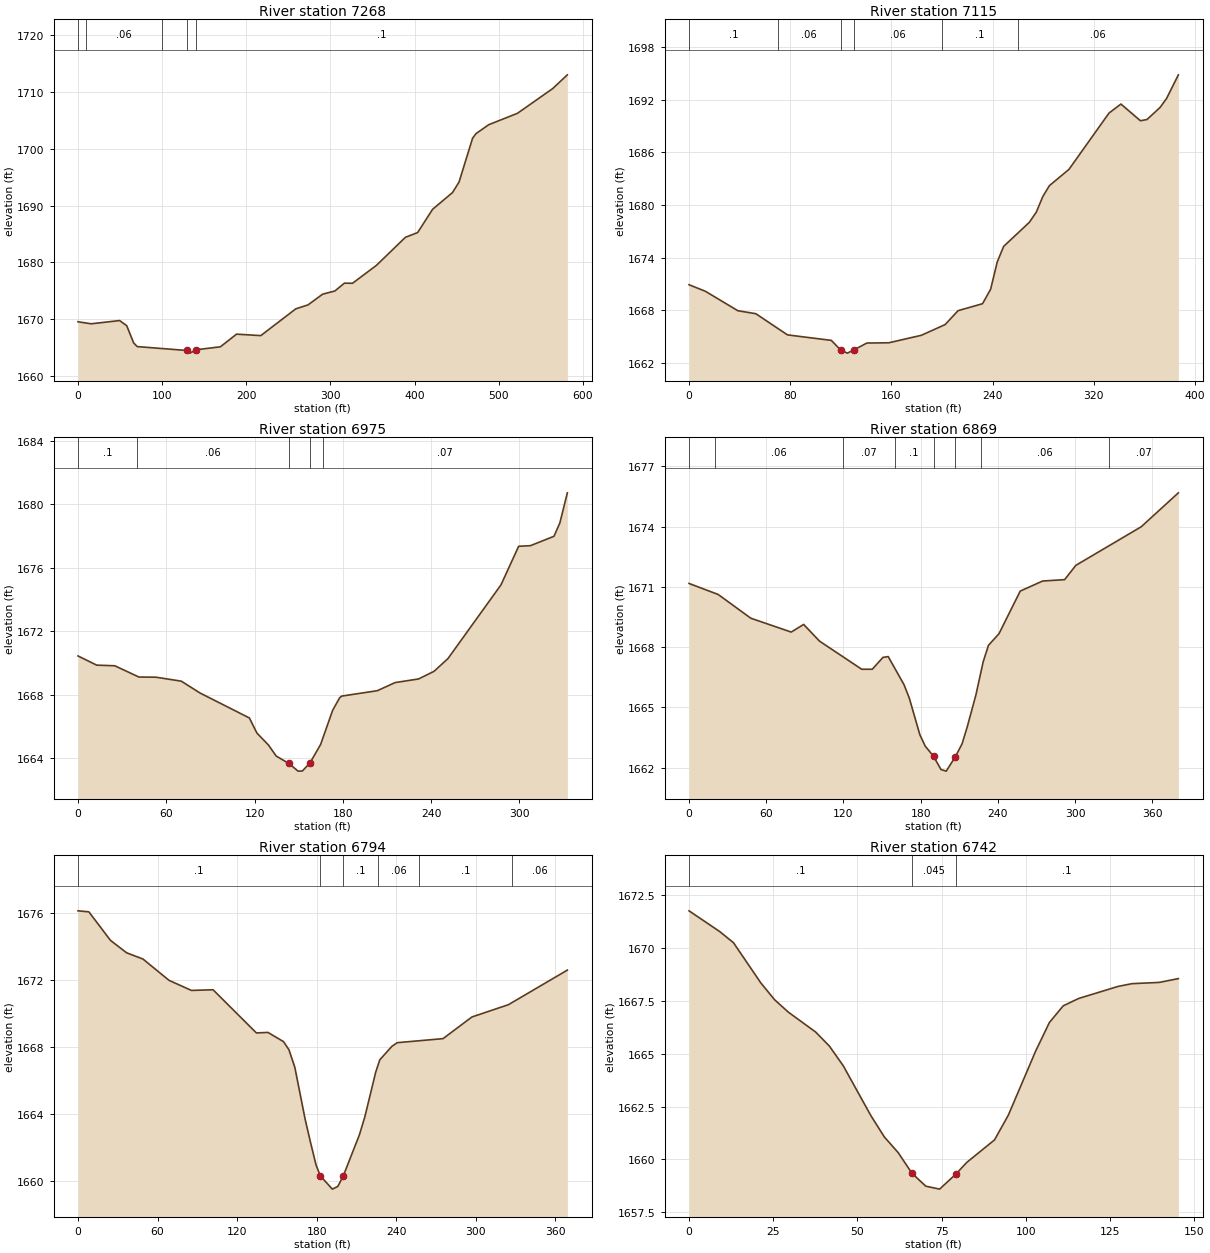
Type RM Length L Ch R = 1 ,7268    ,145.1,152.9,157.4
XS GIS Cut Line= 3
2155256.86397461647697.0168808792155505.27145025647773.502238717
2155679.50533909 648043.83741265
#Sta/Elev= 30
       0 1669.57    15.6 1669.21    49.5 1669.78    57.9 1668.87    66.2 1665.83
    70.4  1665.2129.29791664.515   133.2 1664.05139.99781664.638   169.2 1665.16
   188.4 1667.39   217.2 1667.13   258.8 1671.84   273.4 1672.54   290.7 1674.42
   305.2 1674.98   316.6 1676.36   326.2 1676.34   354.7  1679.5   389.1 1684.43
   403.6 1685.26   421.3 1689.34   445.1 1692.31   452.8 1694.15   468.9 1701.86
     473 1702.67     488 1704.23   522.2 1706.24   564.1 1710.59   581.5 1713.01
#Mann= 5 ,-1,0
       0      .1       0      10     .06       0     100      .1       0
   129.3    .045       0     140      .1       0
Bank Sta=129.2979,139.9978
XS Rating Curve= 0 ,0
Exp/Cntr(USF)=0,0
Exp/Cntr=0.3,0.1

Type RM Length L Ch R = 1 ,7115    ,139.6,139.7,138.8
XS GIS Cut Line= 2
  2155202.901902647732.1755241572155503.49312731647975.681175524
#Sta/Elev= 30
       0 1670.92      13 1670.17    38.6 1667.96    52.8 1667.62    77.8 1665.21
   112.5 1664.58     120 1663.46   125.2 1663.13   130.3  1663.5   140.6 1664.28
     158 1664.31   183.6 1665.16   202.4 1666.38   212.7 1667.97     232 1668.76
   238.4 1670.41   243.6 1673.51   248.7 1675.29     269 1678.03   274.5 1679.19
   279.6 1680.95   284.8  1682.2   300.3 1684.06     332 1690.48   341.4  1691.5
   356.8  1689.6     362 1689.74   372.3 1691.11   377.4 1692.12   386.8 1694.83
#Mann= 6 ,-1,0
       0      .1       0      70     .06       0     120    .045       0
   130.3     .06       0     200      .1       0     260     .06       0
Bank Sta=120,130.3
XS Rating Curve= 0 ,0
Exp/Cntr(USF)=0,0
Exp/Cntr=0.3,0.1

Type RM Length L Ch R = 1 ,6975    ,80.9,106.8,120.4
XS GIS Cut Line= 4
2155203.42280786647756.8377408492155177.08807305647870.369708707
2155229.75754267647905.4826884572155229.75754267648058.224150369
#Sta/Elev= 30
       0 1670.44    12.7 1669.86      25 1669.82    41.4 1669.11      53  1669.1
    70.2 1668.85      83  1668.1   116.5 1666.53   121.6 1665.58   129.5 1664.82
   134.7 1664.13   143.2 1663.67   149.6 1663.18   152.5 1663.19   157.7  1663.7
   164.9 1664.86   173.1 1667.02   177.9 1667.81   179.3 1667.91   203.5 1668.25
   215.5 1668.76   231.5 1668.99     242 1669.47   251.5 1670.28   287.5 1674.92
   299.5 1677.35   307.5 1677.39   323.5 1677.98   327.5 1678.82   332.6 1680.72
#Mann= 5 ,-1,0
       0      .1       0      40     .06       0   143.2    .045       0
   157.7     .06       0  166.55     .07       0
Bank Sta=143.2,157.7
XS Rating Curve= 0 ,0
Exp/Cntr(USF)=0,0
Exp/Cntr=0.3,0.1

Type RM Length L Ch R = 1 ,6869    ,82,74.2,73.7
XS GIS Cut Line= 4
  2155188.728697647778.4300438162155148.68014791647950.812929032
2155131.26773526648028.0079584382155084.25422111648142.929881915
#Sta/Elev= 30
       0 1671.17    22.7 1670.62      48 1669.44    79.4 1668.75    89.1 1669.13
   101.4  1668.3   134.2  1666.9   142.4  1666.9   150.7 1667.49   154.8 1667.53
   167.1 1666.13   171.2 1665.46   179.4 1663.64   183.5 1663.08     190 1662.57
   195.8 1661.91   199.9 1661.83     2071662.548   212.2 1663.19   216.2 1664.03
   222.9 1665.61   228.6 1667.27   232.7 1668.09   240.9 1668.67   257.4 1670.79
   274.8 1671.29   291.9 1671.36   300.6 1672.07   351.4 1673.99   380.3 1675.68
#Mann= 8 ,-1,0
       0      .1       0      20     .06       0     120     .07       0
     160      .1       0     190    .045       0     207      .1       0
  226.97     .06       0  326.11     .07       0
Bank Sta=190,207
XS Rating Curve= 0 ,0
Exp/Cntr(USF)=0,0
Exp/Cntr=0.3,0.1

Type RM Length L Ch R = 1 ,6794    ,59.5,52.3,48.3
XS GIS Cut Line= 4
2155108.39944354647777.0796554532155090.40661714647871.687097507
2155059.06427438648019.6926050152155010.30951896648131.132045963
#Sta/Elev= 30
       0  1676.1     8.2 1676.04    24.5 1674.34    36.7  1673.6      49 1673.23
    68.7 1671.96    85.6 1671.36   101.9  1671.4   134.6 1668.83   143.3 1668.86
   155.1 1668.31   159.2 1667.82   163.6 1666.78   171.4 1663.68   175.5 1662.29
   179.6 1660.97   182.8 1660.32   191.9 1659.53     196 1659.69     200 1660.29
   212.3 1662.76   216.4 1663.83   224.6 1666.49   227.7 1667.23   236.8 1668.03
   240.9 1668.25   275.4 1668.49   297.2 1669.78   324.7 1670.51   369.2 1672.57
#Mann= 6 ,-1,0
       0      .1       0   182.8    .045       0     200      .1       0
   226.3     .06       0  257.59      .1       0  327.59     .06       0
Bank Sta=182.8,200
XS Rating Curve= 0 ,0
Exp/Cntr(USF)=0,0
Exp/Cntr=0.3,0.1

Type RM Length L Ch R = 1 ,6742    ,83.3,77,71.5
XS GIS Cut Line= 2
2155004.91555363647908.2658274572155033.42069156648050.791517093
#Sta/Elev= 27
       0 1671.77     9.1 1670.79    13.2 1670.26    21.3 1668.36    25.4 1667.56
    29.5 1666.97    37.6 1666.03    41.7 1665.36    45.8 1664.43      54 1662.07
      58 1661.06    62.1 1660.32    66.2 1659.34    70.3 1658.73    74.4 1658.59
    79.21659.297    82.5 1659.86    90.7 1660.92    94.8 1662.09   102.9 1665.12
     107 1666.48   111.1 1667.27   115.7 1667.62   127.4 1668.19   131.5 1668.32
   139.6 1668.38   145.3 1668.56
#Mann= 3 ,-1,0
       0      .1       0    66.2    .045       0    79.2      .1       0
Bank Sta=66.2,79.2
XS Rating Curve= 0 ,0
Exp/Cntr(USF)=0,0
Exp/Cntr=0.3,0.1

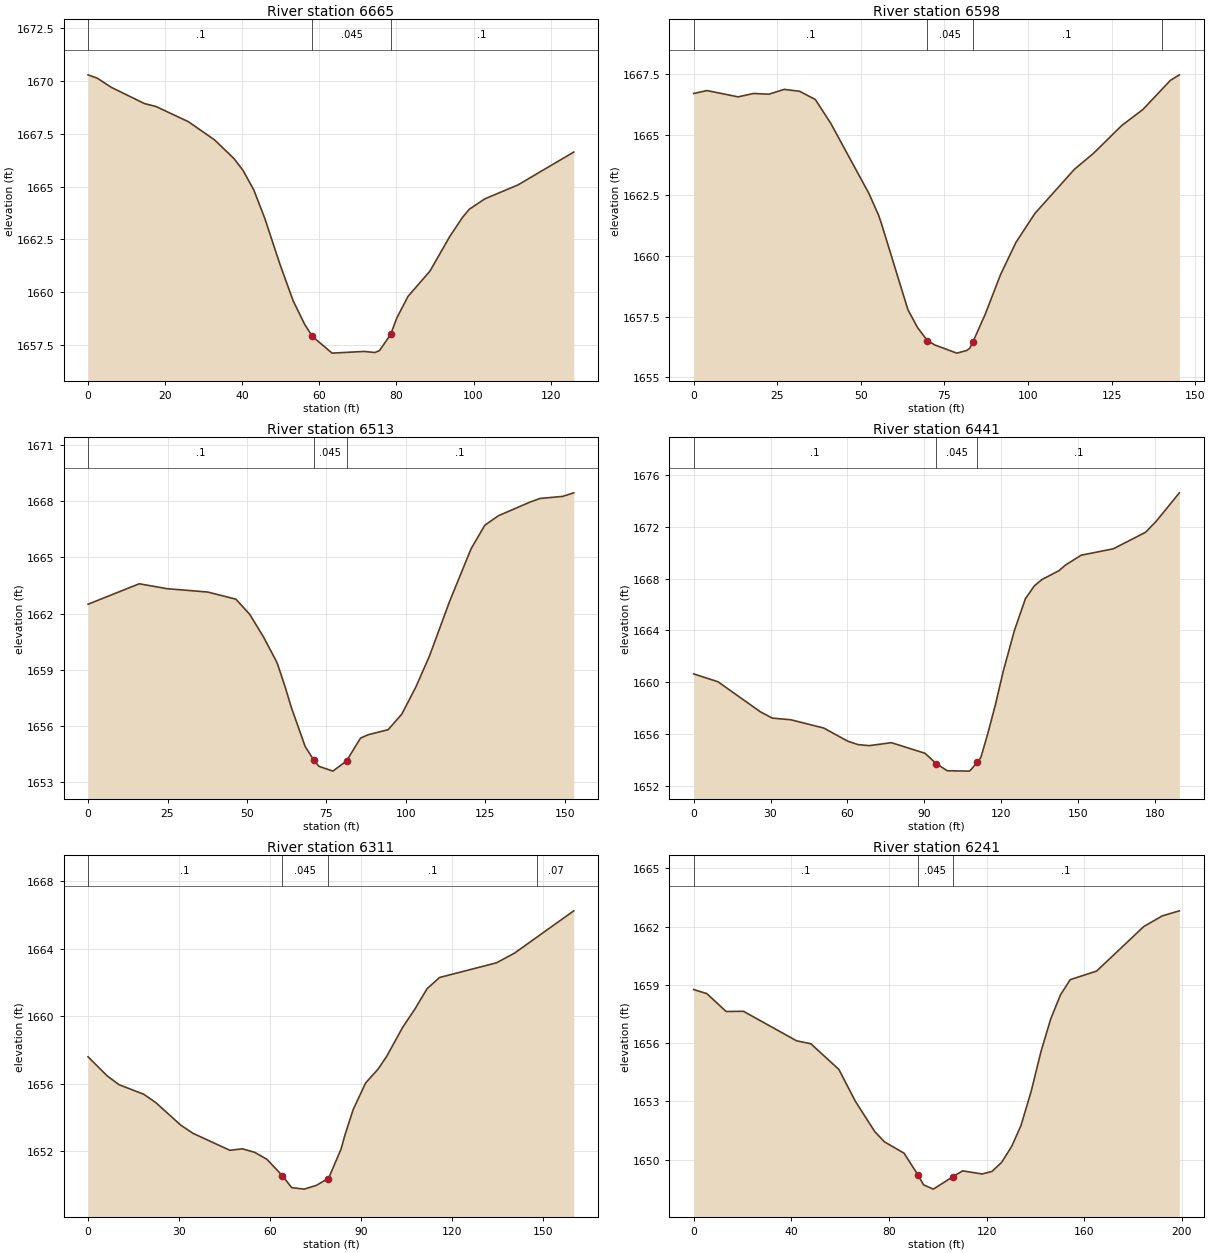
Type RM Length L Ch R = 1 ,6665    ,73.9,67.5,63
XS GIS Cut Line= 2
2154909.57078195 647963.31023173 2154987.2227094 648062.58674658
#Sta/Elev= 29
       0  1670.3     2.4 1670.14       6 1669.71    14.6 1668.94    17.6  1668.8
      26 1668.08    32.8 1667.22    37.9 1666.32    40.2 1665.77      43 1664.84
    45.9 1663.47    49.7 1661.36    53.2 1659.59    56.2 1658.47    58.2  1657.9
    63.3 1657.11    71.6 1657.19    74.4 1657.14    75.6 1657.23    78.5    1658
    80.1 1658.78      83  1659.8    88.7    1661    93.8 1662.63    97.2 1663.56
    98.9 1663.93   102.9 1664.42   111.5 1665.08     126 1666.64
#Mann= 3 ,-1,0
       0      .1       0    58.2    .045       0    78.5      .1       0
Bank Sta=58.2,78.5
XS Rating Curve= 0 ,0
Exp/Cntr(USF)=0,0
Exp/Cntr=0.3,0.1

Type RM Length L Ch R = 1 ,6598    ,86.5,85,83.9
XS GIS Cut Line= 2
2154844.69701977648033.0986728622154970.51280096648105.835921366
#Sta/Elev= 30
       0 1666.71       4 1666.83    13.3 1666.57    17.9 1666.71    22.5 1666.68
    27.1 1666.88    31.7  1666.8    36.4 1666.46      41 1665.48    52.4 1662.59
    55.3 1661.69    56.1 1661.37    64.1 1657.78      67 1657.04    69.9 1656.51
    72.1 1656.33    78.7 1655.99    81.7  1656.1    82.6 1656.19    83.51656.442
    87.2 1657.59    91.8 1659.23    96.4 1660.56   102.1 1661.76   113.9 1663.58
   119.7 1664.25     128 1665.38   134.4 1666.05   142.6 1667.25   145.3 1667.48
#Mann= 4 ,-1,0
       0      .1       0    69.9    .045       0    83.5      .1       0
     140     .06       0
Bank Sta=69.9,83.5
XS Rating Curve= 0 ,0
Exp/Cntr(USF)=0,0
Exp/Cntr=0.3,0.1

Type RM Length L Ch R = 1 ,6513    ,72,72,72.8
XS GIS Cut Line= 2
2154805.37958814648118.614086643 2154945.9394062 648178.57316987
#Sta/Elev= 30
       0  1662.5    16.1 1663.59    24.8 1663.33    37.6 1663.15    46.5 1662.77
    50.9 1661.95    55.2 1660.75      59 1659.53    59.6 1659.31      62 1658.09
    63.9 1657.02    68.3 1654.91    71.1 1654.17    72.6 1653.86      77  1653.6
    81.3 1654.14    85.7 1655.36    88.1 1655.54    94.4 1655.81    98.7 1656.64
   103.1 1658.08   107.4 1659.74   113.8 1662.68   120.5 1665.46   124.8 1666.71
   129.1 1667.22   139.1 1667.95   142.2 1668.14   149.3 1668.25   152.8 1668.44
#Mann= 3 ,-1,0
       0      .1       0    71.1    .045       0    81.3      .1       0
Bank Sta=71.1,81.3
XS Rating Curve= 0 ,0
Exp/Cntr(USF)=0,0
Exp/Cntr=0.3,0.1

Type RM Length L Ch R = 1 ,6441    ,114.8,130,149
XS GIS Cut Line= 4
2154780.72575312648160.0277179342154789.48371101648189.486303578
2154900.15245167648237.2569830012154936.77663923648248.403474866
#Sta/Elev= 30
       0 1660.64     9.5 1660.03    26.1  1657.7    30.7 1657.22      38 1657.09
    50.8 1656.45    60.2 1655.43    64.2 1655.17    68.5 1655.09    77.2 1655.32
    90.3  1654.5    94.7  1653.7      99 1653.15   107.7 1653.12   110.7 1653.79
   112.1 1654.17   114.7 1655.94   117.8 1658.26   120.8 1660.81   125.2 1663.99
   129.5 1666.45     133 1667.45     136 1667.94   142.6 1668.62   145.1 1669.05
   151.3 1669.82   163.8 1670.31   176.4 1671.59   180.6 1672.45   189.6 1674.64
#Mann= 3 ,-1,0
       0      .1       0    94.7    .045       0   110.7      .1       0
Bank Sta=94.7,110.7
XS Rating Curve= 0 ,0
Exp/Cntr(USF)=0,0
Exp/Cntr=0.3,0.1

Type RM Length L Ch R = 1 ,6311    ,72.4,69.8,67.1
XS GIS Cut Line= 3
 2154756.8404134648183.1168796552154735.34360766 648299.35886625
2154771.96779522   648320.059494
#Sta/Elev= 30
       0 1657.61     6.2  1656.5    10.2 1655.96    18.4 1655.39    22.4 1654.89
    30.6 1653.56    34.6 1653.08    46.8 1652.07    50.9 1652.16      55 1651.95
      59 1651.54    64.1 1650.57    67.2 1649.86    71.3 1649.77    75.3 1649.99
    79.11650.384    79.4 1650.42    83.5 1652.15    84.7 1652.93    87.5 1654.49
    91.6 1656.06    95.7 1656.88    98.5 1657.62   103.8 1659.35   107.9 1660.45
   111.9 1661.65     116 1662.31   134.8 1663.18   140.7 1663.75   160.3 1666.26
#Mann= 4 ,-1,0
       0      .1       0    64.1    .045       0    79.1      .1       0
  148.21     .07       0
Bank Sta=64.1,79.1
XS Rating Curve= 0 ,0
Exp/Cntr(USF)=0,0
Exp/Cntr=0.3,0.1

Type RM Length L Ch R = 1 ,6241    ,66.7,66.7,66.2
XS GIS Cut Line= 5
2154713.84680192648167.1933198472154684.38821628648195.059549511
2154673.24172441648210.9831093182154677.22261437648305.728290174
2154711.45826795648333.594519837
#Sta/Elev= 30
       0 1658.76     5.4 1658.55    13.3 1657.63    20.4 1657.64    42.2 1656.12
      48 1655.97    59.5 1654.65    66.2 1653.02    74.2 1651.45    78.2 1650.92
    86.2 1650.34    91.8 1649.24    94.2 1648.71    98.2 1648.49   106.2 1649.13
   110.2 1649.43   118.2 1649.27   122.2  1649.4   126.2 1649.87   130.3 1650.69
   134.1 1651.76   138.3 1653.53   142.3 1655.57   146.3 1657.25   150.3 1658.49
   154.3 1659.27   165.1 1659.71   184.4    1662     192 1662.55     199 1662.81
#Mann= 3 ,-1,0
       0      .1       0    91.8    .045       0   106.2      .1       0
Bank Sta=91.8,106.2
XS Rating Curve= 0 ,0
Exp/Cntr(USF)=0,0
Exp/Cntr=0.3,0.1