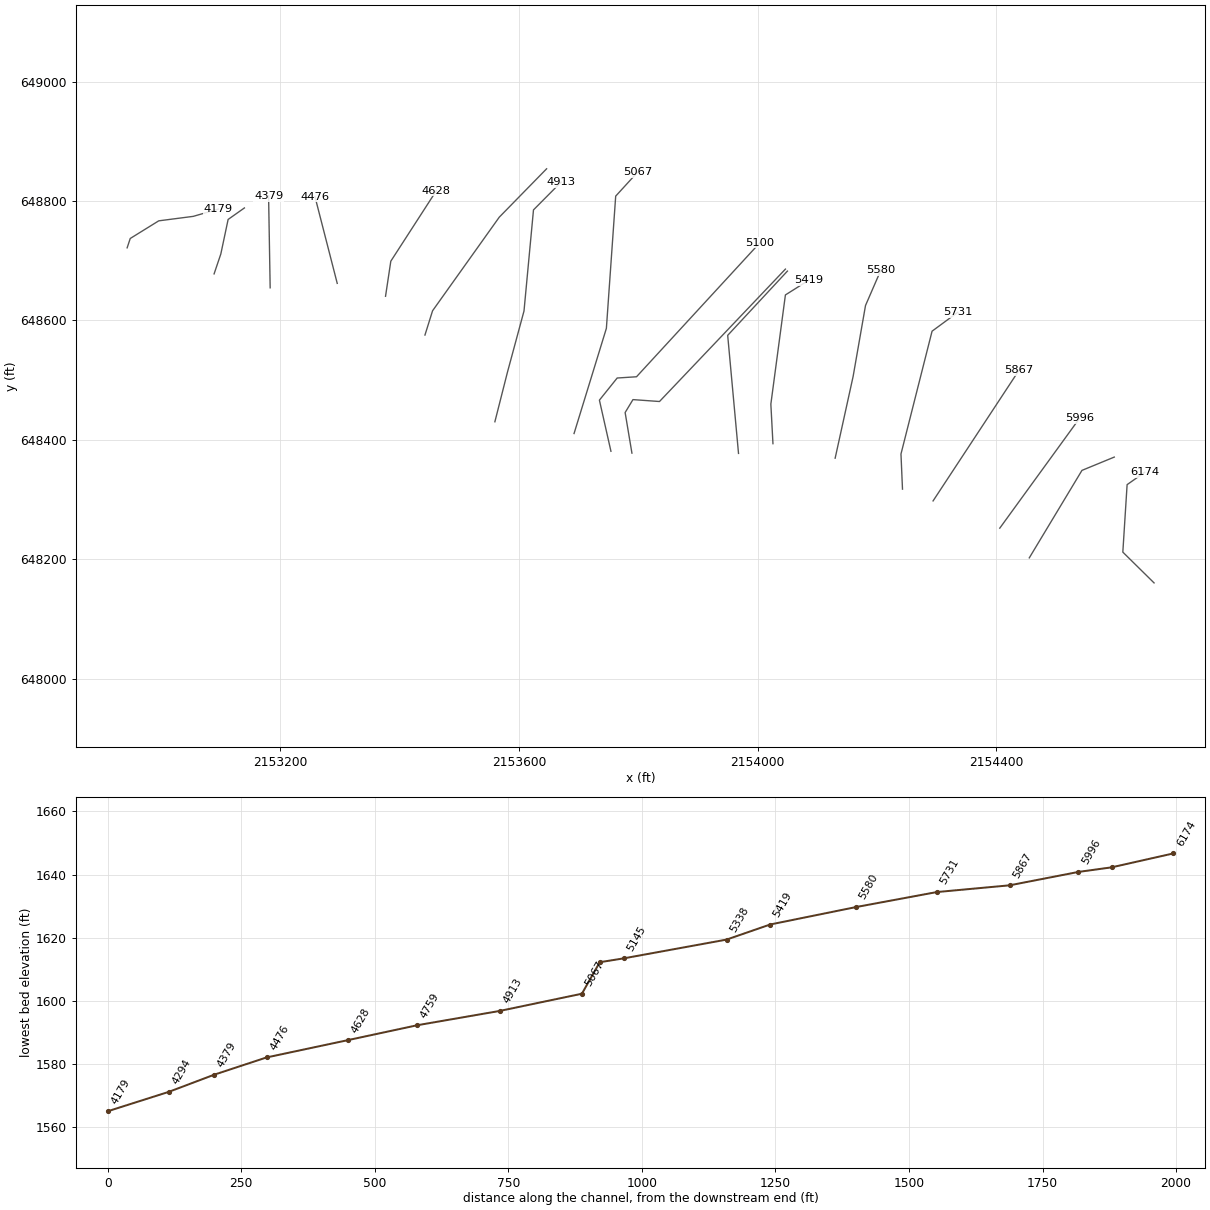
HEC-RAS study LYNNCMPRN.prj: LYNNCMPRN

--- LYNNCMPRN.g01 (geometry) --- (continued)

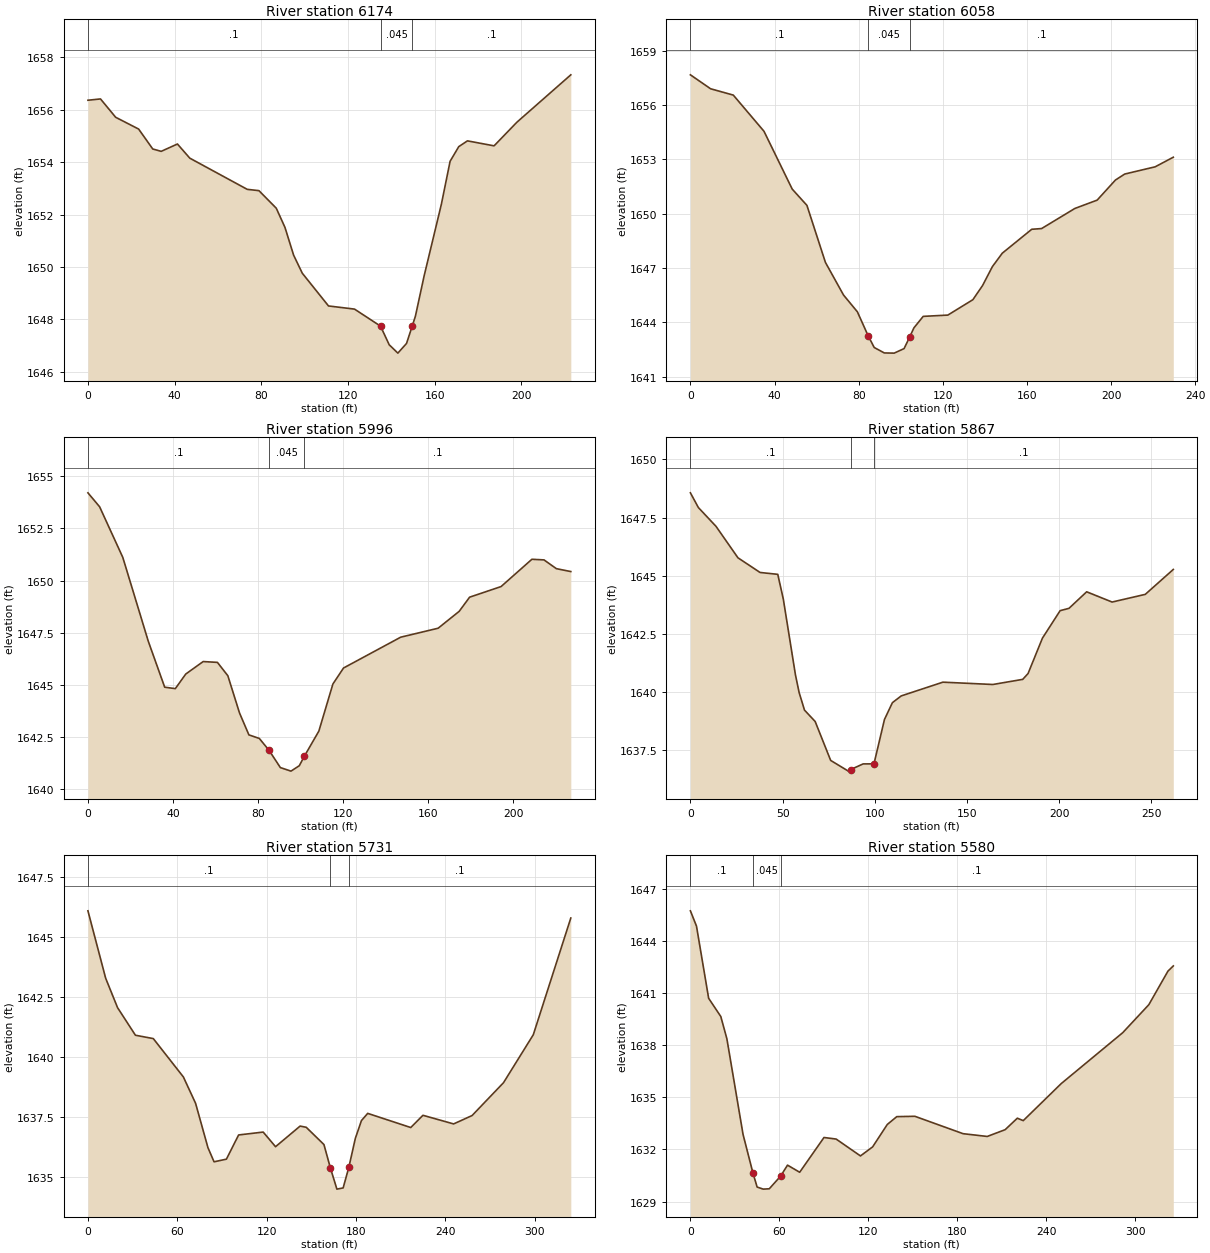
Type RM Length L Ch R = 1 ,6174    ,123,115.7,108.6
XS GIS Cut Line= 4
2154664.27803413648160.1829726412154611.93601915648211.779287309
2154619.10162107648324.8365619432154648.56020671648345.537189693
#Sta/Elev= 30
       0 1656.36     5.8 1656.41    12.8 1655.71    23.4 1655.26    29.9  1654.5
    33.8 1654.41    41.3 1654.69      47 1654.15    73.5 1652.96    78.9 1652.91
    86.9 1652.24    90.9 1651.51    94.9 1650.45    98.9 1649.76     111 1648.51
     123 1648.39     135 1647.74     139 1647.03     143 1646.71     147 1647.08
   149.71647.759   151.1 1648.12   155.1 1649.65   163.1  1652.4   167.1 1654.03
   171.1 1654.59   175.1 1654.81   187.4 1654.62   197.9 1655.52   222.8 1657.33
#Mann= 3 ,-1,0
       0      .1       0     135    .045       0   149.7      .1       0
Bank Sta=135,149.7
XS Rating Curve= 0 ,0
Exp/Cntr(USF)=0,0
Exp/Cntr=0.3,0.1

Type RM Length L Ch R = 1 ,6058    ,63.9,62.1,60.7
XS GIS Cut Line= 3
2154455.21514926648202.1532565522154543.46471198648348.721901654
2154597.60481533648371.014885385
#Sta/Elev= 30
       0 1657.67     9.6  1656.9    20.4 1656.55      35 1654.55    48.4 1651.36
    55.4 1650.46    64.2 1647.31    72.8 1645.51    79.4 1644.58    84.5 1643.26
    87.4 1642.61    92.2 1642.31    96.9  1642.3   101.6 1642.55   104.21643.178
   106.3  1643.7   110.7 1644.33   122.4  1644.4   134.3 1645.25   138.9 1646.03
   143.6 1647.08   148.3 1647.82   162.3 1649.14     167 1649.18   182.8 1650.29
   193.4 1650.75   202.1 1651.86   206.5 1652.19     221 1652.59   229.6 1653.12
#Mann= 3 ,-1,0
       0      .1       0    84.5    .045       0   104.2      .1       0
Bank Sta=84.5,104.2
XS Rating Curve= 0 ,0
Exp/Cntr(USF)=0,0
Exp/Cntr=0.3,0.1

Type RM Length L Ch R = 1 ,5996    ,126.9,128.9,128.8
XS GIS Cut Line= 2
2154405.77295121648251.9307553232154539.20227426648435.688682681
#Sta/Elev= 30
       0 1654.21     5.5 1653.54    16.4 1651.11    28.4 1647.08    36.1 1644.88
    41.1 1644.81      46 1645.51    54.2 1646.11    60.9 1646.07    65.8 1645.43
    71.3 1643.64    75.7 1642.59    80.6 1642.42    85.21641.846    90.5 1641.02
    95.5 1640.85    99.4 1641.11   101.81641.568   108.6 1642.77   115.2 1645.03
   120.2  1645.8   147.1 1647.28   164.7 1647.71   174.6 1648.52   179.5  1649.2
   194.3 1649.71   208.8 1651.02   214.5 1650.99   220.3 1650.57   227.1 1650.43
#Mann= 3 ,-1,0
       0      .1       0    85.2    .045       0   101.8      .1       0
Bank Sta=85.2,101.8
XS Rating Curve= 0 ,0
Exp/Cntr(USF)=0,0
Exp/Cntr=0.3,0.1

Type RM Length L Ch R = 1 ,5867    ,131.4,136.1,138.6
XS GIS Cut Line= 2
2154293.99663234648297.5776289982154437.95984931648516.448536106
#Sta/Elev= 30
       0 1648.56     4.3 1647.93    13.9 1647.12    25.8 1645.77    37.8 1645.14
    47.4 1645.06    50.4    1644      57 1640.74      59 1639.98    61.9 1639.23
    67.7 1638.74    76.1 1637.07    85.7 1636.61    86.91636.675    93.7 1636.92
    99.61636.923   105.3 1638.83   109.6 1639.55   114.4 1639.84     137 1640.43
   164.1 1640.33   180.3 1640.55   183.2  1640.8     191 1642.32   200.6  1643.5
   205.4  1643.6     215 1644.31   228.8 1643.87   246.8  1644.2     262 1645.27
#Mann= 3 ,-1,0
       0      .1       0    86.9    .045       0    99.6      .1       0
Bank Sta=86.9,99.6
XS Rating Curve= 0 ,0
Exp/Cntr(USF)=0,0
Exp/Cntr=0.3,0.1

Type RM Length L Ch R = 1 ,5731    ,152.7,151.7,148.5
XS GIS Cut Line= 4
 2154242.7712296648317.3095439572154240.22750132648376.178617618
2154292.32527826648581.9570579872154335.11788003648613.413534901
#Sta/Elev= 30
       0 1646.09    11.9 1643.28    19.9 1642.05    31.9  1640.9    43.9 1640.76
    64.1 1639.16    72.3 1638.06    80.6 1636.21    84.7 1635.62      93 1635.73
   101.2 1636.74   117.7 1636.86     126 1636.25   142.5 1637.11   146.6 1637.06
   158.5 1636.34   162.81635.371   167.2 1634.48   171.4 1634.53   175.21635.385
   179.6  1636.6   183.7 1637.34   187.9 1637.64   216.8 1637.05     225 1637.56
   245.6  1637.2     258 1637.55   279.1 1638.92   299.1 1640.92   324.3 1645.79
#Mann= 3 ,-1,0
       0      .1       0   162.8    .045       0   175.2      .1       0
Bank Sta=162.8,175.2
XS Rating Curve= 0 ,0
Exp/Cntr(USF)=0,0
Exp/Cntr=0.3,0.1

Type RM Length L Ch R = 1 ,5580    ,160.3,160.4,162
XS GIS Cut Line= 4
2154129.93440781648369.1818669922154160.02993585648506.044863538
 2154180.8101814648624.9938553012154206.60634829648684.468351182
#Sta/Elev= 30
       0 1645.73     4.1 1644.85    12.3  1640.7    20.5 1639.65    24.6 1638.37
    35.5 1632.87    42.2 1630.64      45 1629.84    49.1 1629.72    53.2 1629.74
    60.81630.464    65.5  1631.1    73.7 1630.69    90.1 1632.69    98.3  1632.6
   114.7 1631.63   122.9 1632.15   132.8 1633.44   139.2 1633.89   151.4 1633.91
   183.9 1632.91   200.2 1632.75   212.3 1633.14   220.5  1633.8   224.5 1633.66
   250.1 1635.79   291.6 1638.72   309.2 1640.33   322.1 1642.26   325.7 1642.56
#Mann= 3 ,-1,0
       0      .1       0    42.2    .045       0    60.8      .1       0
Bank Sta=42.2,60.8
XS Rating Curve= 0 ,0
Exp/Cntr(USF)=0,0
Exp/Cntr=0.3,0.1

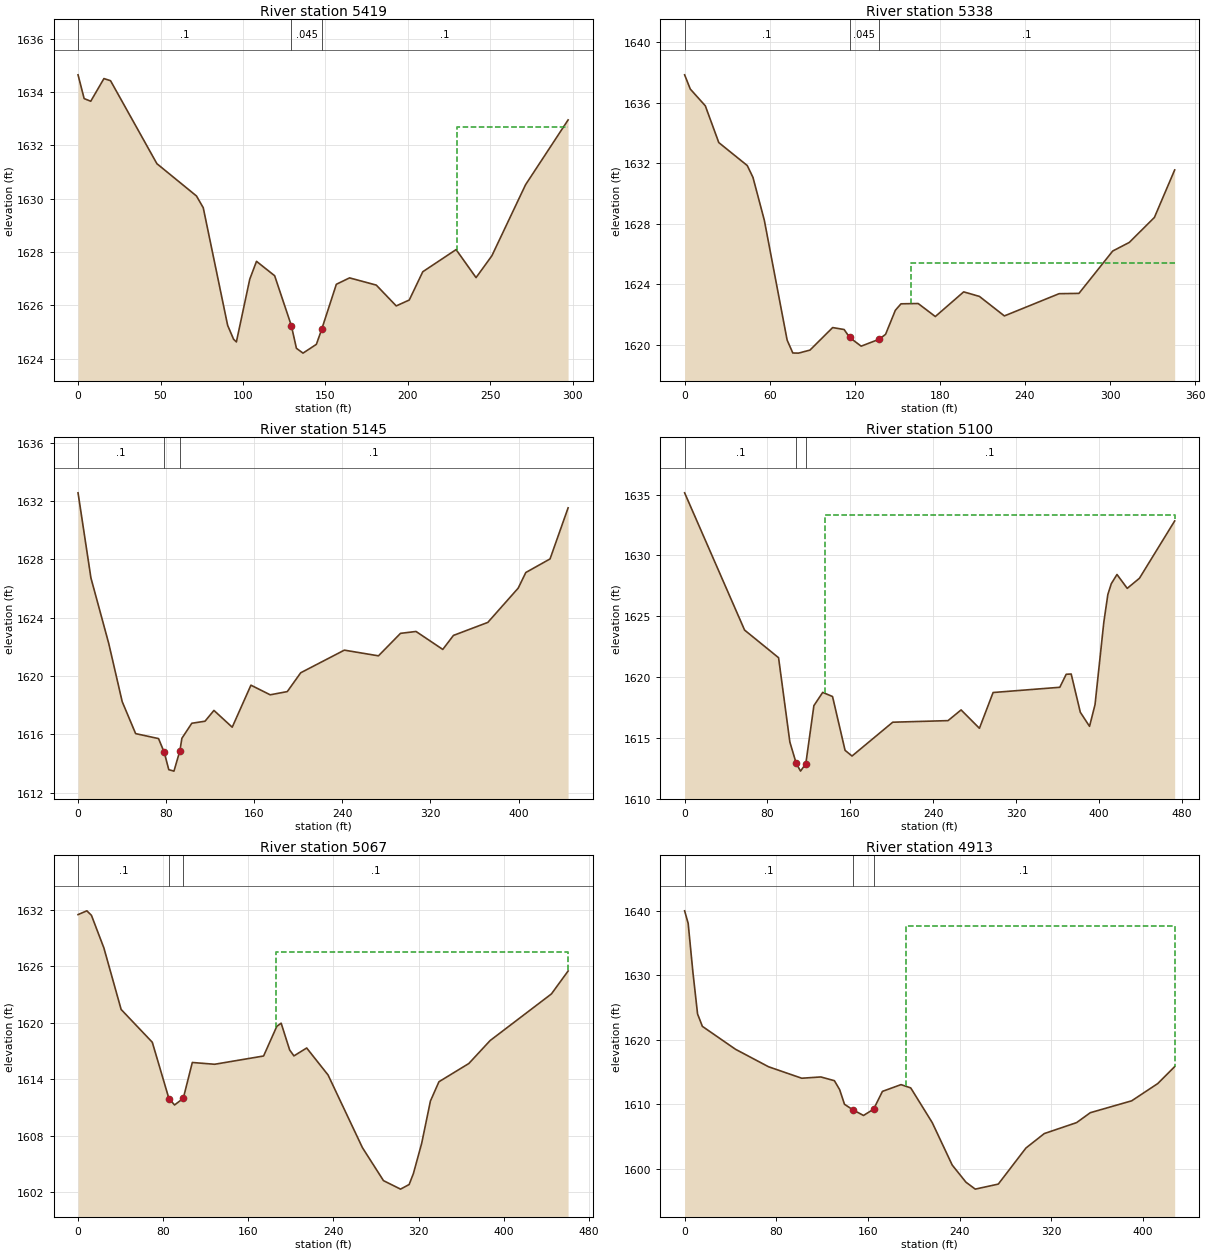
Type RM Length L Ch R = 1 ,5419    ,80.5,81.7,84.6
XS GIS Cut Line= 4
2154025.72593714648393.484328328 2154022.2099883648459.771029187
2154046.59453163648642.6866326942154085.64419581648667.296175899
#Sta/Elev= 30
       0 1634.64     3.7 1633.75     7.7 1633.65    15.7  1634.5    19.7 1634.42
    47.8 1631.31    71.8  1630.1    75.9 1629.66    90.7 1625.25    94.3 1624.73
      96 1624.63   104.1 1626.98   108.2 1627.65   119.2 1627.11   129.31625.245
   132.4 1624.39   136.4 1624.21   144.5 1624.54   147.7  1625.1   156.6 1626.79
   164.6 1627.03   180.8 1626.76   192.9 1625.98   200.8  1626.2     209 1627.26
   229.2 1628.09   241.3 1627.04   250.9 1627.86   271.3 1630.52   297.1 1632.95
#Mann= 3 ,-1,0
       0      .1       0   129.3    .045       0   147.7      .1       0
#XS Ineff= 2 , 0
                          229.69         1632.68
Permanent Ineff=
       F       F
Bank Sta=129.3,147.7
XS Rating Curve= 0 ,0
Exp/Cntr(USF)=0,0
Exp/Cntr=0.3,0.1

Type RM Length L Ch R = 1 ,5338    ,198.6,192.6,175.6
XS GIS Cut Line= 3
2153968.03113699648377.1670497652153949.88943079648574.970169023
2154049.96142307 648682.64997359
#Sta/Elev= 30
       0 1637.83       4 1636.89    14.6 1635.78    24.1 1633.35    44.2 1631.83
    48.2 1631.05    56.2 1628.22    72.3 1620.29    76.3 1619.44    80.3 1619.43
    88.4 1619.63   104.4 1621.12   112.5 1620.99   116.41620.464   124.5 1619.89
   137.11620.346   141.7 1620.67   148.6 1622.26   152.6 1622.69   164.7 1622.71
   176.8 1621.85   196.8 1623.48   207.9 1623.18   225.5 1621.89   264.1 1623.36
   278.1 1623.38   301.9 1626.18   313.6 1626.75   331.3  1628.4   345.6 1631.54
#Mann= 3 ,-1,0
       0      .1       0   116.4    .045       0   137.1      .1       0
#XS Ineff= 2 , 0
                          159.72         1625.37
Permanent Ineff=
       F       F
Bank Sta=116.4,137.1
XS Rating Curve= 0 ,0
Exp/Cntr(USF)=0,0
Exp/Cntr=0.3,0.1

Type RM Length L Ch R = 1 ,5145    ,46.4,44.8,54.2
XS GIS Cut Line= 5
2153789.43886532648377.6357131262153778.05593509 648445.64230076
2153791.17303803648467.3107503852153835.62039698648464.120206647
2154046.60203555648685.967692186
#Sta/Elev= 30
       0 1632.56    11.7 1626.73    27.9 1622.23    40.1 1618.25    52.3 1616.06
    73.1 1615.72    78.3 1614.77    82.4 1613.59    87.1 1613.49    92.51614.895
    94.3 1615.74   103.3 1616.77   115.3 1616.91   123.4 1617.65     140  1616.5
     157 1619.38   174.5 1618.72     190 1618.94   202.2 1620.23   241.8 1621.78
   272.8 1621.39   292.8 1622.93   306.9 1623.06   331.2 1621.83   340.9 1622.79
   372.1 1623.68   399.7 1626.03   406.6  1627.1   428.6 1628.03     445 1631.53
#Mann= 3 ,-1,0
       0      .1       0    78.3    .045       0    92.5      .1       0
Bank Sta=78.3,92.5
XS Rating Curve= 0 ,0
Exp/Cntr(USF)=0,0
Exp/Cntr=0.3,0.1

Type RM Length L Ch R = 1 ,5100    ,29.7,33.4,37.4
XS GIS Cut Line= 5
2153754.28498867648380.7339411692153734.95721063648466.403011405
2153764.73243626648503.4914503492153797.11952379648505.580939867
2154003.84781599648730.181811641
#Sta/Elev= 30
       0 1635.14    57.9 1623.86    90.7 1621.59   101.6 1614.66   107.7 1612.92
   111.9 1612.27     117 1612.88   124.8 1617.65   133.3 1618.74   142.8  1618.4
   154.9 1613.98   161.6 1613.51   200.9 1616.29   254.3 1616.42   266.9  1617.3
   284.6 1615.79   297.8 1618.73   362.2 1619.16   368.4 1620.23   373.2 1620.25
     382 1617.11   390.9 1615.95   396.2 1617.73   404.7 1624.51   408.6 1626.79
   411.9 1627.67   417.4 1628.43   427.3 1627.29   439.1 1628.12   473.1 1632.83
#Mann= 3 ,-1,0
       0      .1       0   107.7    .045       0     117      .1       0
#XS Ineff= 2 , 0
                          135.15          1633.3
Permanent Ineff=
       F       F
Bank Sta=107.7,117
XS Rating Curve= 0 ,0
Exp/Cntr(USF)=0,0
Exp/Cntr=0.3,0.1

Type RM Length L Ch R = 1 ,5067    ,150.9,153.3,153.5
XS GIS Cut Line= 4
2153692.46343416648410.4800939032153746.64255023648586.731607995
2153762.23951655 648808.233717052153798.77094767 648848.21908724
#Sta/Elev= 30
       0  1631.5     8.3  1631.9    12.6 1631.42    24.3 1627.95    40.5 1621.41
    69.8 1617.92    85.41611.939    90.7 1611.25    98.91611.954   107.4 1615.77
   128.4 1615.58   174.4 1616.46   186.8 1619.61   190.9 1619.95   198.9  1617.1
   202.9 1616.47   214.9 1617.31     235 1614.44   267.3 1606.71   287.1  1603.2
   303.1  1602.3   311.2 1602.79   315.2 1603.96     323 1607.18   331.2 1611.67
   339.2 1613.72   367.3 1615.66   387.3  1618.1   444.9 1623.06   460.6  1625.5
#Mann= 3 ,-1,0
       0      .1       0    85.4    .045       0    98.9      .1       0
#XS Ineff= 2 , 0
                           186.2         1627.54
Permanent Ineff=
       F       F
Bank Sta=85.4,98.9
XS Rating Curve= 0 ,0
Exp/Cntr(USF)=0,0
Exp/Cntr=0.3,0.1

Type RM Length L Ch R = 1 ,4913    ,158.7,154.9,149.8
XS GIS Cut Line= 5
2153559.81811679648430.1898240822153580.88509578648513.257636186
2153608.61597519648615.7973995682153624.50072418648785.144555323
2153670.71224463648831.698158015
#Sta/Elev= 30
       0 1640.01     3.1 1638.06     7.2 1630.55    11.3 1624.02    15.5  1622.1
    44.4 1618.55    73.2 1615.84   102.2 1614.06   118.8 1614.26   130.7 1613.68
   135.3 1612.28   139.5 1610.02     147 1609.15   156.1 1608.29   164.91609.263
   172.6 1612.02   188.8 1613.07   197.3 1612.56   216.1 1607.17   233.5  1600.6
   245.5 1597.94   253.6 1596.87   273.7 1597.65   297.8 1603.24   313.8 1605.48
     342 1607.18     354 1608.72   390.1 1610.56   412.8 1613.23   427.6 1615.86
#Mann= 3 ,-1,0
       0      .1       0     147    .045       0   164.9      .1       0
#XS Ineff= 2 , 0
                          193.39         1637.66
Permanent Ineff=
       F       F
Bank Sta=147,164.9
XS Rating Curve= 0 ,0
Exp/Cntr(USF)=0,0
Exp/Cntr=0.3,0.1

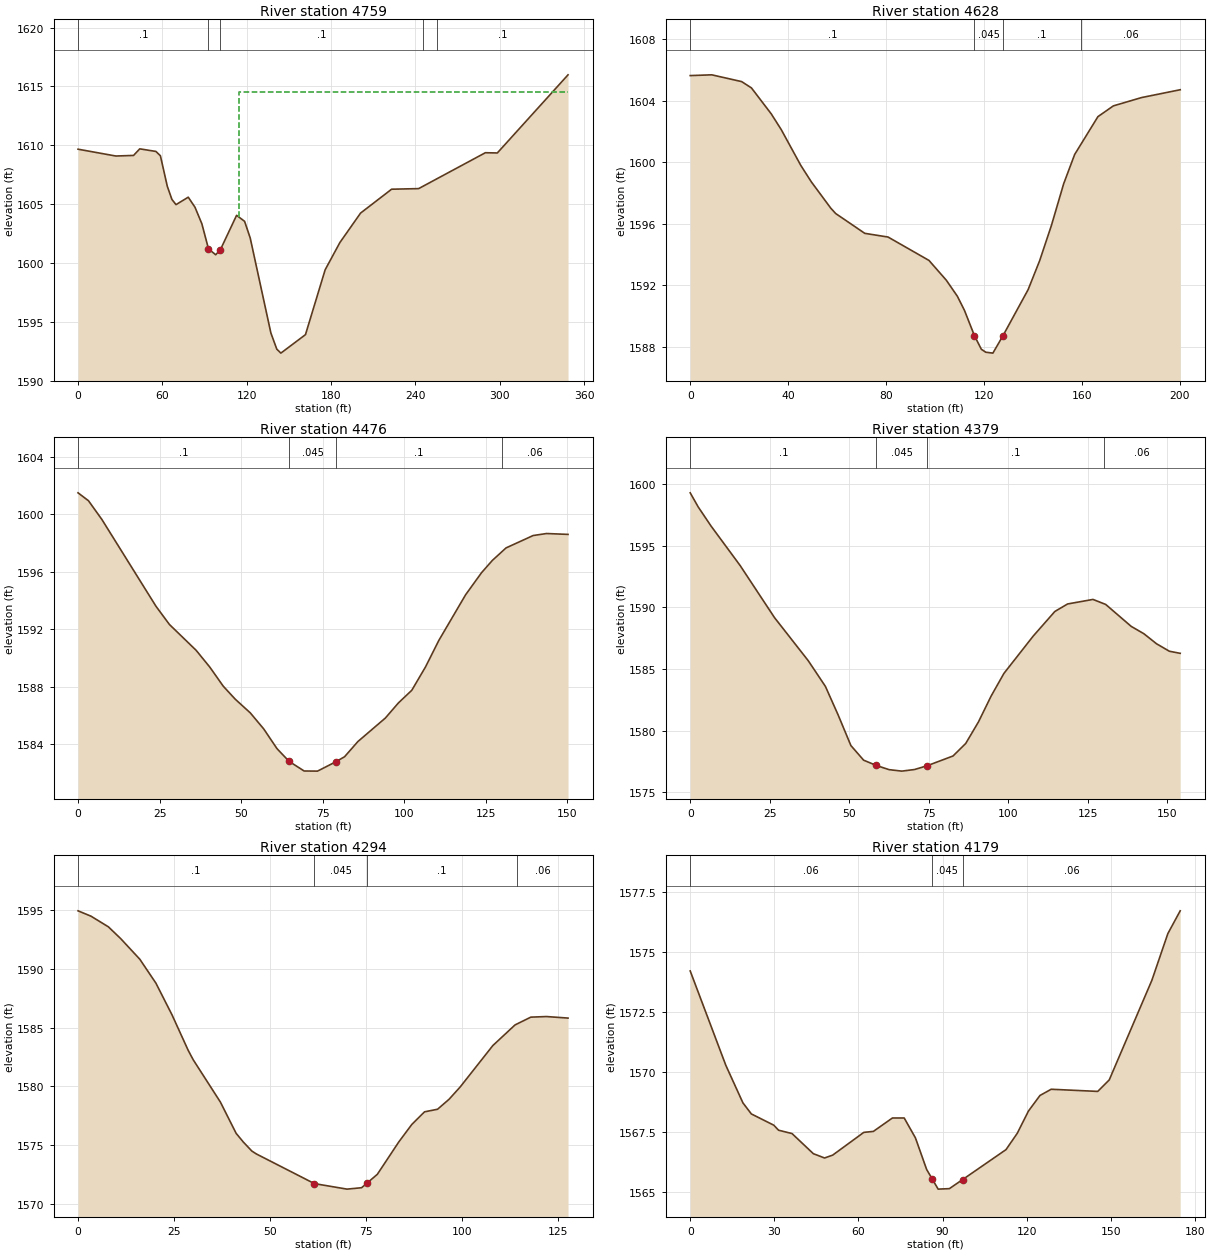
Type RM Length L Ch R = 1 ,4759    ,128.7,130.2,131
XS GIS Cut Line= 4
2153442.67007398648575.4940890382153455.41688937648616.153556989
2153567.17106656648772.9751880412153646.48002759648854.030711177
#Sta/Elev= 30
       0 1609.66    26.9 1609.08    39.5 1609.13    43.9 1609.69    55.4 1609.47
    58.6  1609.1    63.5 1606.51    66.8 1605.39    69.7 1604.95    78.4 1605.58
    83.2 1604.73    88.1 1603.32    92.81601.195    97.9 1600.69   101.2  1601.1
   112.8 1604.04   118.5 1603.53   122.5 1602.11   137.2 1594.04   141.4 1592.67
   144.3 1592.33   161.8  1593.9   175.8 1599.41   186.3 1601.73     201 1604.23
   223.1 1606.26   242.3 1606.31   289.8 1609.36   298.3 1609.34   348.6 1615.98
#Mann= 5 ,-1,0
       0      .1       0    92.8    .045       0   101.2      .1       0
  245.18     .06       0  255.18      .1       0
#XS Ineff= 2 , 0
                          114.23         1614.54
Permanent Ineff=
       F       F
Bank Sta=92.8,101.2
XS Rating Curve= 0 ,0
Exp/Cntr(USF)=0,0
Exp/Cntr=0.3,0.1

Type RM Length L Ch R = 1 ,4628    ,141.4,152,159.4
XS GIS Cut Line= 3
2153376.61204566648640.4417443542153385.45011453648699.214768933
2153461.80496932648817.373048383
#Sta/Elev= 30
       0 1605.65     8.8  1605.7      21 1605.26      25 1604.85    33.1 1603.16
    37.2 1602.13    45.2  1599.8    49.5 1598.73    57.4 1597.03    59.4 1596.68
    71.3 1595.39    80.8 1595.15    97.5 1593.63   104.6 1592.34   109.1  1591.3
     112 1590.38116.07981588.733   118.9 1587.85   120.7 1587.66   123.6  1587.6
127.6798 1588.72     138 1591.73   142.7 1593.61   147.5  1595.9   152.5 1598.61
     157 1600.52   166.5 1602.98   172.8 1603.68   184.3 1604.22   200.1 1604.73
#Mann= 4 ,-1,0
       0      .1       0116.0798    .045       0127.6798      .1       0
  159.43     .06       0
Bank Sta=116.0798,127.6798
XS Rating Curve= 0 ,0
Exp/Cntr(USF)=0,0
Exp/Cntr=0.3,0.1

Type RM Length L Ch R = 1 ,4476    ,100,97.5,94.1
XS GIS Cut Line= 2
 2153295.6888207648662.0691934692153258.33726066648807.543690477
#Sta/Elev= 30
       0 1601.48     3.2 1600.93     7.3 1599.63    23.9 1593.59      28 1592.33
    36.2 1590.53    40.4 1589.36    44.5 1588.04    48.2 1587.13    52.8 1586.18
    56.9 1585.07      61 1583.69    64.71582.808    69.3 1582.14    73.4 1582.13
    79.11582.789    81.7 1583.13    85.8 1584.19    94.2 1585.82    98.2 1586.87
   102.3 1587.75   106.5 1589.37   110.6 1591.22   118.8 1594.39   123.7 1595.93
     127 1596.78   131.2 1597.65   139.5 1598.51   143.6 1598.65   150.2 1598.59
#Mann= 4 ,-1,0
       0      .1       0    64.7    .045       0    79.1      .1       0
     130     .06       0
Bank Sta=64.7,79.1
XS Rating Curve= 0 ,0
Exp/Cntr(USF)=0,0
Exp/Cntr=0.3,0.1

Type RM Length L Ch R = 1 ,4379    ,87,85.3,79.3
XS GIS Cut Line= 2
2153183.32159748648654.6401997892153180.66767085648808.567944597
#Sta/Elev= 30
       0 1599.31     2.5 1598.17     6.5 1596.63    15.7  1593.4    26.5 1589.17
    37.1 1585.67    42.5 1583.58    46.5 1581.26    50.5 1578.78    54.5 1577.59
    58.5 1577.16    62.5 1576.82    66.5  1576.7    70.5 1576.83    74.5 1577.14
    82.6 1577.93    86.6 1578.95    90.6  1580.7    94.6 1582.81    98.6 1584.64
   107.8 1587.67   114.6 1589.67   118.6 1590.28   126.6 1590.65   130.6 1590.24
   138.6 1588.46   142.6 1587.86   146.6 1587.04   150.6 1586.44     154 1586.27
#Mann= 4 ,-1,0
       0      .1       0    58.5    .045       0    74.5      .1       0
     130     .06       0
Bank Sta=58.5,74.5
XS Rating Curve= 0 ,0
Exp/Cntr(USF)=0,0
Exp/Cntr=0.3,0.1

Type RM Length L Ch R = 1 ,4294    ,125.4,114.4,98.3
XS GIS Cut Line= 4
2153089.37182498648677.9692587852153100.65506838648711.348853835
2153112.87858206648769.1754762442153140.14642027648788.451017047
#Sta/Elev= 30
       0 1594.94     3.4 1594.48     7.9 1593.58    11.1 1592.58    16.1 1590.82
    20.3 1588.78    24.5 1586.08    28.7 1583.07      30 1582.27    37.1 1578.66
    41.2    1576    43.1 1575.25    45.3 1574.49    46.5 1574.24    61.6 1571.72
    70.1 1571.25    73.9 1571.37    75.21571.731      78 1572.51    83.6 1575.27
      87 1576.76    90.3 1577.83    93.7 1578.05    96.7  1578.9    99.6 1579.95
   108.1 1583.47   113.9 1585.23     118 1585.89   122.1 1585.94   127.7 1585.81
#Mann= 4 ,-1,0
       0      .1       0    61.6    .045       0    75.2      .1       0
  114.34     .06       0
Bank Sta=61.6,75.2
XS Rating Curve= 0 ,0
Exp/Cntr(USF)=0,0
Exp/Cntr=0.3,0.1

Type RM Length L Ch R = 1 ,4179    ,89.8,103.2,110
XS GIS Cut Line= 5
2152943.67694462 648721.597799922152948.87823758648737.284156973
2152996.61022504648766.8282876172153054.53481099648774.346962801
2153096.37683859648786.523462967
#Sta/Elev= 30
       0 1574.22    12.7 1570.28    18.8 1568.71    21.8 1568.25    29.8 1567.78
    31.5 1567.57    36.3 1567.43    43.9 1566.59    47.9 1566.41    50.8 1566.53
    61.9 1567.48    65.3 1567.52    72.1 1568.08    76.3 1568.08    80.3 1567.25
    84.3 1565.93    86.3 1565.53    88.4 1565.11    92.4 1565.13    97.11565.507
   112.6 1566.76   116.6 1567.44   120.6 1568.37   124.7 1569.02   128.7 1569.28
   145.3 1569.19   149.4 1569.67   164.6 1573.83   170.3 1575.78   174.7 1576.73
#Mann= 3 ,-1,0
       0     .06       0    86.3    .045       0    97.1     .06       0
Bank Sta=86.3,97.1
XS Rating Curve= 0 ,0
Exp/Cntr(USF)=0,0
Exp/Cntr=0.3,0.1