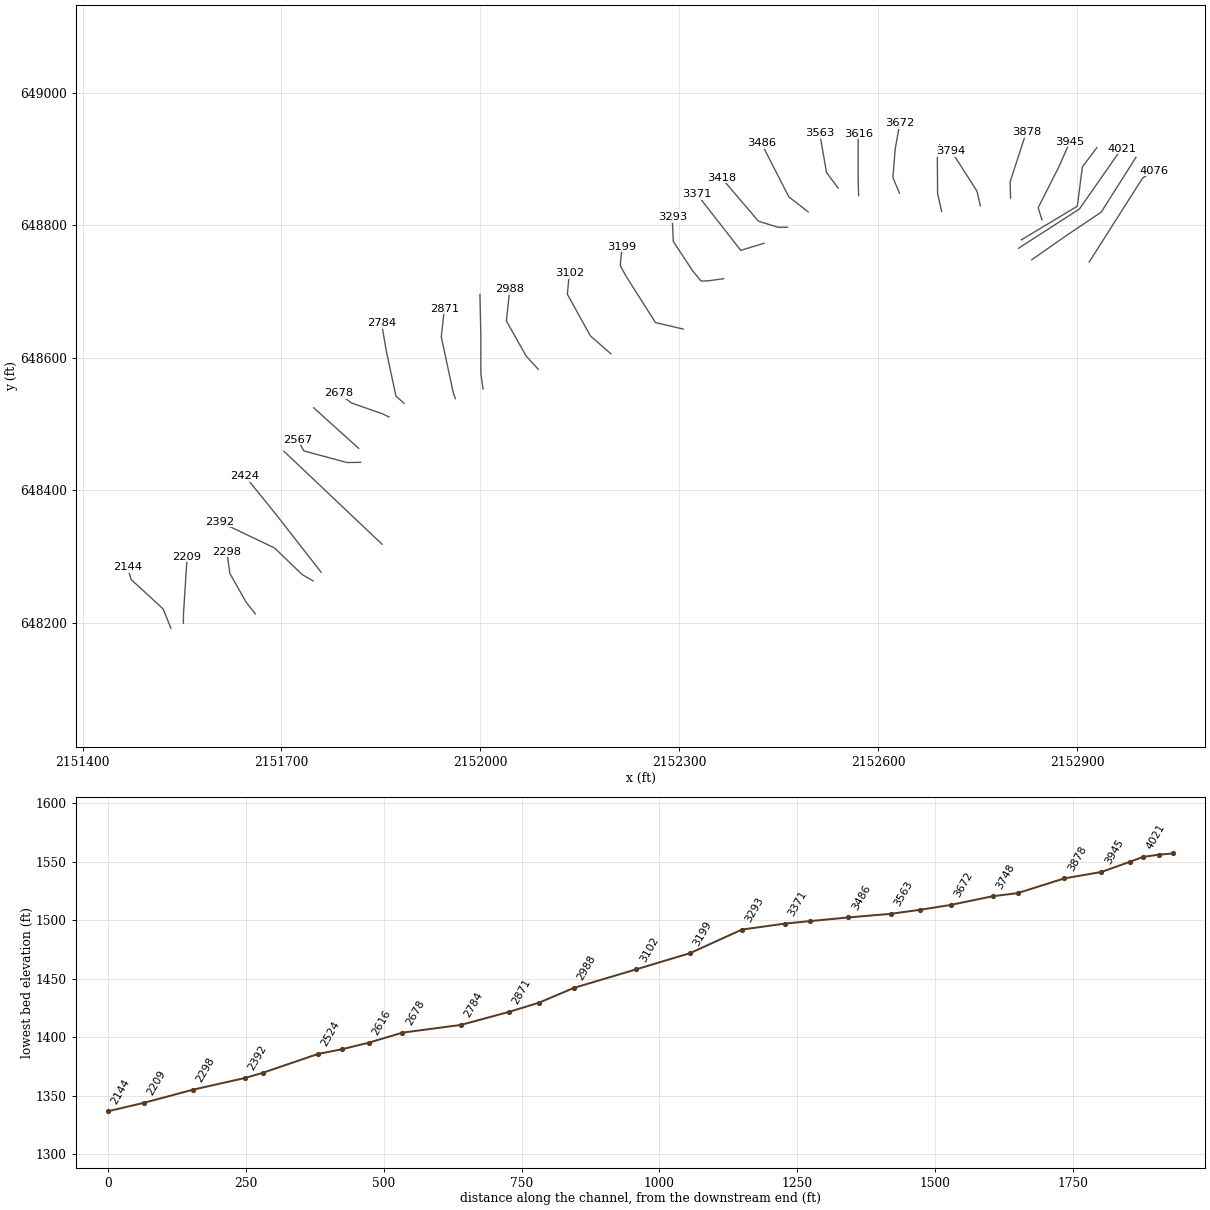
HEC-RAS study LYNNCMPRN.prj: LYNNCMPRN

--- LYNNCMPRN.g01 (geometry) --- (continued)

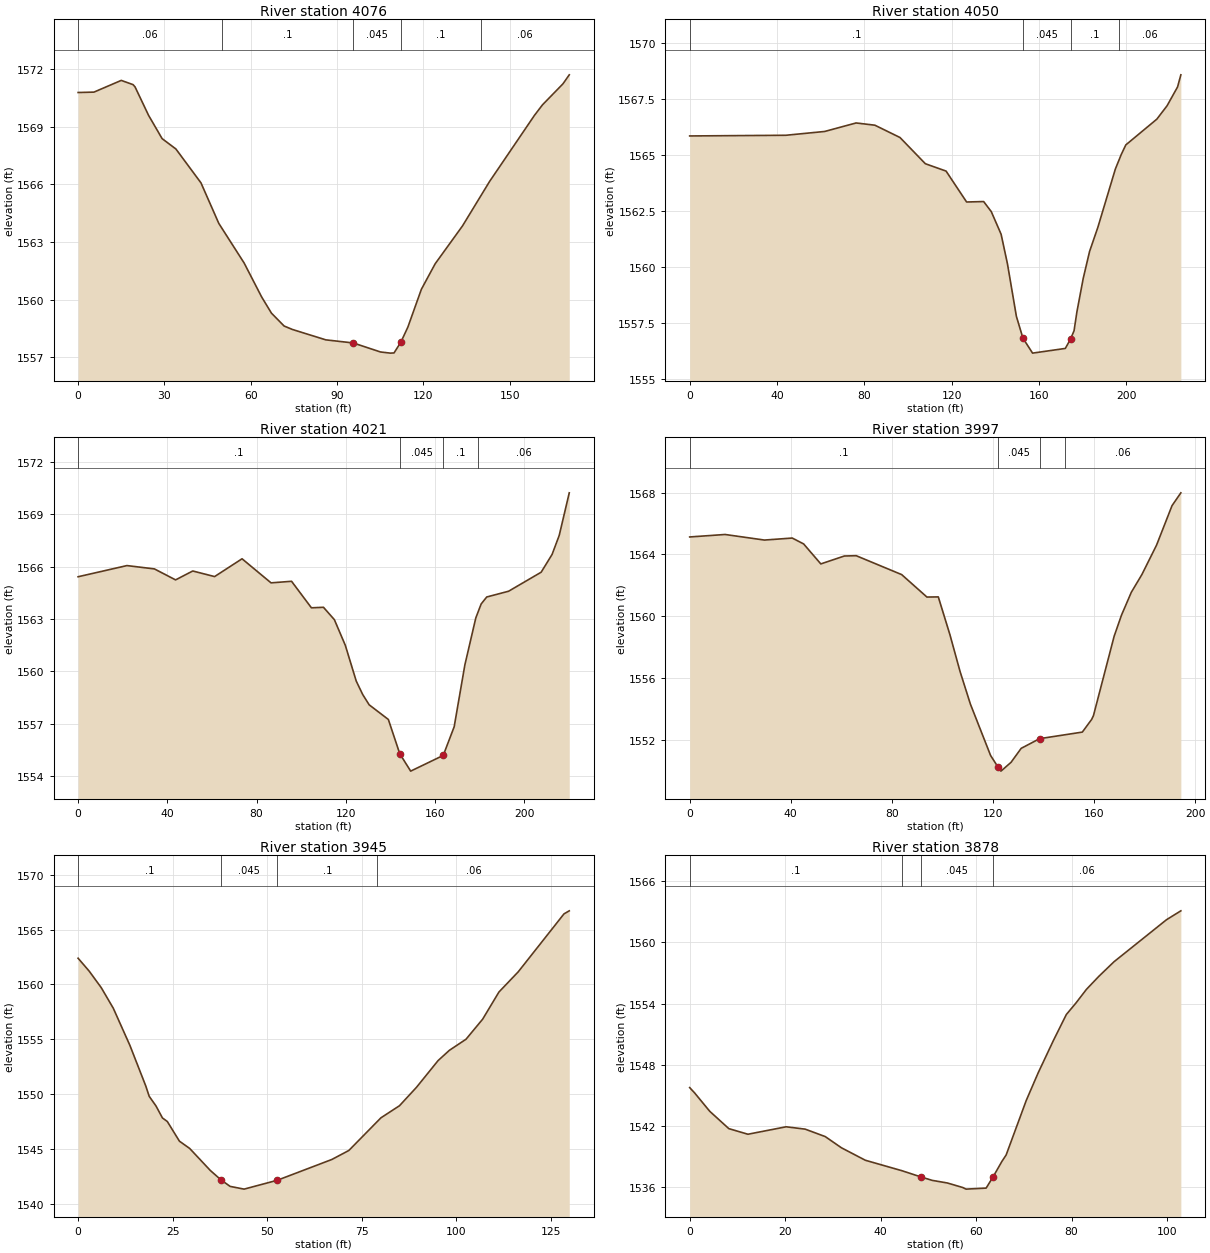
Type RM Length L Ch R = 1 ,4076    ,25.4,25.6,27.3
XS GIS Cut Line= 3
2152917.92881824 648744.515993262152998.66042475648871.325544988
2153015.79685066648882.369019463
#Sta/Elev= 30
       0 1570.78     5.5  1570.8      15 1571.41    19.1 1571.19    19.8 1571.07
    24.5 1569.59    29.2 1568.38      34 1567.84    42.7 1566.08    48.9 1563.97
    57.7 1561.91    63.8 1560.14    67.2  1559.3    71.6 1558.63    74.5 1558.45
    86.1 1557.91    95.6 1557.75   105.1 1557.28   108.5 1557.22   109.8 1557.23
   112.2  1557.8   114.6 1558.57   119.3 1560.54   124.1 1561.87   133.6 1563.84
     143 1566.15   158.6 1569.59   161.4 1570.14   168.5 1571.23   170.7  1571.7
#Mann= 5 ,-1,0
       0     .06       0      50      .1       0    95.6    .045       0
   112.2      .1       0     140     .06       0
Bank Sta=95.6,112.2
XS Rating Curve= 0 ,0
Exp/Cntr(USF)=0,0
Exp/Cntr=0.3,0.1

Type RM Length L Ch R = 1 ,4050    ,29.7,29,28.4
XS GIS Cut Line= 4
 2152831.3672385648747.987708265 2152883.8833978648784.642963101
2152935.97543392648819.6138404952152988.49461418648902.455024049
#Sta/Elev= 30
       0 1565.86      44 1565.89    61.8 1566.06    76.2 1566.44    84.8 1566.34
    96.3 1565.79   107.9 1564.62   117.4 1564.29   126.8 1562.91   134.6 1562.93
   138.1 1562.48   142.6 1561.47   145.5 1560.15   149.6  1557.8   152.61556.827
     157 1556.16     172 1556.37   174.4 1556.79     176 1557.16   177.3    1558
   180.2  1559.5   183.1  1560.7   186.9 1561.78   194.9 1564.38   197.6 1565.03
   199.7 1565.46   213.9 1566.61   218.6 1567.21   223.4 1568.05   224.9 1568.59
#Mann= 4 ,-1,0
       0      .1       0   152.6    .045       0   174.4      .1       0
  196.79     .06       0
Bank Sta=152.6,174.4
XS Rating Curve= 0 ,0
Exp/Cntr(USF)=0,0
Exp/Cntr=0.3,0.1

Type RM Length L Ch R = 1 ,4021    ,17.6,24.6,31.8
XS GIS Cut Line= 3
2152811.47702276648765.308211851 2152903.2944159648824.545239682
   2152966.76266648915.516389565
#Sta/Elev= 30
       0 1565.43    21.9 1566.07    34.2 1565.88    43.7 1565.25    51.4 1565.76
    61.2 1565.44    73.5 1566.46    86.5 1565.08    95.7 1565.17   104.6 1563.65
     110 1563.68   114.9 1562.97   119.8  1561.5   124.7 1559.45   127.6 1558.68
   130.5 1558.09   139.1 1557.25   144.2 1555.29   149.1 1554.29   163.7 1555.19
   168.6 1556.83   173.4 1560.38   178.3 1563.07   180.7 1563.87   183.2 1564.27
     193  1564.6   207.6 1565.69   212.5 1566.71   215.7  1567.8   220.2 1570.24
#Mann= 4 ,-1,0
       0      .1       0   144.2    .045       0   163.7      .1       0
  179.27     .06       0
Bank Sta=144.2,163.7
XS Rating Curve= 0 ,0
Exp/Cntr(USF)=0,0
Exp/Cntr=0.3,0.1

Type RM Length L Ch R = 1 ,3997    ,56.3,51.4,48.5
XS GIS Cut Line= 4
2152815.69077611648777.9502099062152900.06726645648828.670909155
2152907.65167008648887.924062483 2152929.4568305648916.839601307
#Sta/Elev= 30
       0 1565.13      14 1565.29    29.6 1564.93    40.6 1565.06    45.1 1564.68
    51.9 1563.39    61.2  1563.9    65.9 1563.92    83.9  1562.7    93.9 1561.25
    98.4 1561.26     103 1558.82     107 1556.45   111.1 1554.34   119.1 1551.02
     122 1550.28   123.2 1550.01   127.2 1550.58   131.2 1551.48   138.51552.106
   155.4 1552.53   159.1 1553.35   159.8 1553.59     168 1558.72   170.9 1560.08
   174.8 1561.56     179 1562.71   184.8 1564.61   190.9 1567.15   194.4 1567.98
#Mann= 4 ,-1,0
       0      .1       0     122    .045       0   138.5      .1       0
  148.45     .06       0
Bank Sta=122,138.5
XS Rating Curve= 0 ,0
Exp/Cntr(USF)=0,0
Exp/Cntr=0.3,0.1

Type RM Length L Ch R = 1 ,3945    ,63.6,67.4,68.2
XS GIS Cut Line= 4
2152846.71744835648808.1111738572152841.00530639 648826.39002816
2152872.23168249648888.0811614332152888.98729893648926.162107898
#Sta/Elev= 30
       0 1562.39     2.9 1561.23     6.1 1559.72     9.3 1557.84    13.7 1554.45
    17.9 1550.75    18.8 1549.81    20.6 1548.93    22.3 1547.84    23.6 1547.51
    26.8 1545.72    29.5 1545.06      35 1543.04    37.81542.193    40.2  1541.6
    43.9 1541.35    52.7 1542.16    67.1 1544.05    71.6 1544.87    80.1 1547.85
      85 1548.95    89.5 1550.63    95.2 1553.06    98.2    1554   102.6 1555.01
     107 1556.84   111.3 1559.31   116.4 1561.15   128.5 1566.43   129.9 1566.71
#Mann= 4 ,-1,0
       0      .1       0    37.8    .045       0    52.7      .1       0
   79.15     .06       0
Bank Sta=37.8,52.7
XS Rating Curve= 0 ,0
Exp/Cntr(USF)=0,0
Exp/Cntr=0.3,0.1

Type RM Length L Ch R = 1 ,3878    ,71.5,84.2,92.7
XS GIS Cut Line= 3
2152799.40791299648840.9937457192152798.64629406648865.365551457
 2152823.0180998648940.004206528
#Sta/Elev= 30
       0 1545.77       1 1545.27     4.2 1543.45     8.2 1541.75    12.2  1541.2
    20.2 1541.93    24.2  1541.7    28.4 1540.97    31.8 1539.87    36.8 1538.65
    44.5 1537.62    48.51537.008    50.8 1536.68      54 1536.42    57.2 1535.98
    57.9 1535.82    62.1 1535.92    63.5 1536.97    65.4 1538.53    66.3 1539.17
    70.5  1544.5      73 1547.21    76.2 1550.39    78.9 1552.93    80.9 1554.05
    83.1 1555.39    85.7 1556.67    88.9 1558.11    99.9 1562.23   102.9  1563.1
#Mann= 4 ,-1,0
       0      .1       0   44.38     .06       0    48.5    .045       0
    63.5     .06       0
Bank Sta=48.5,63.5
XS Rating Curve= 0 ,0
Exp/Cntr(USF)=0,0
Exp/Cntr=0.3,0.1

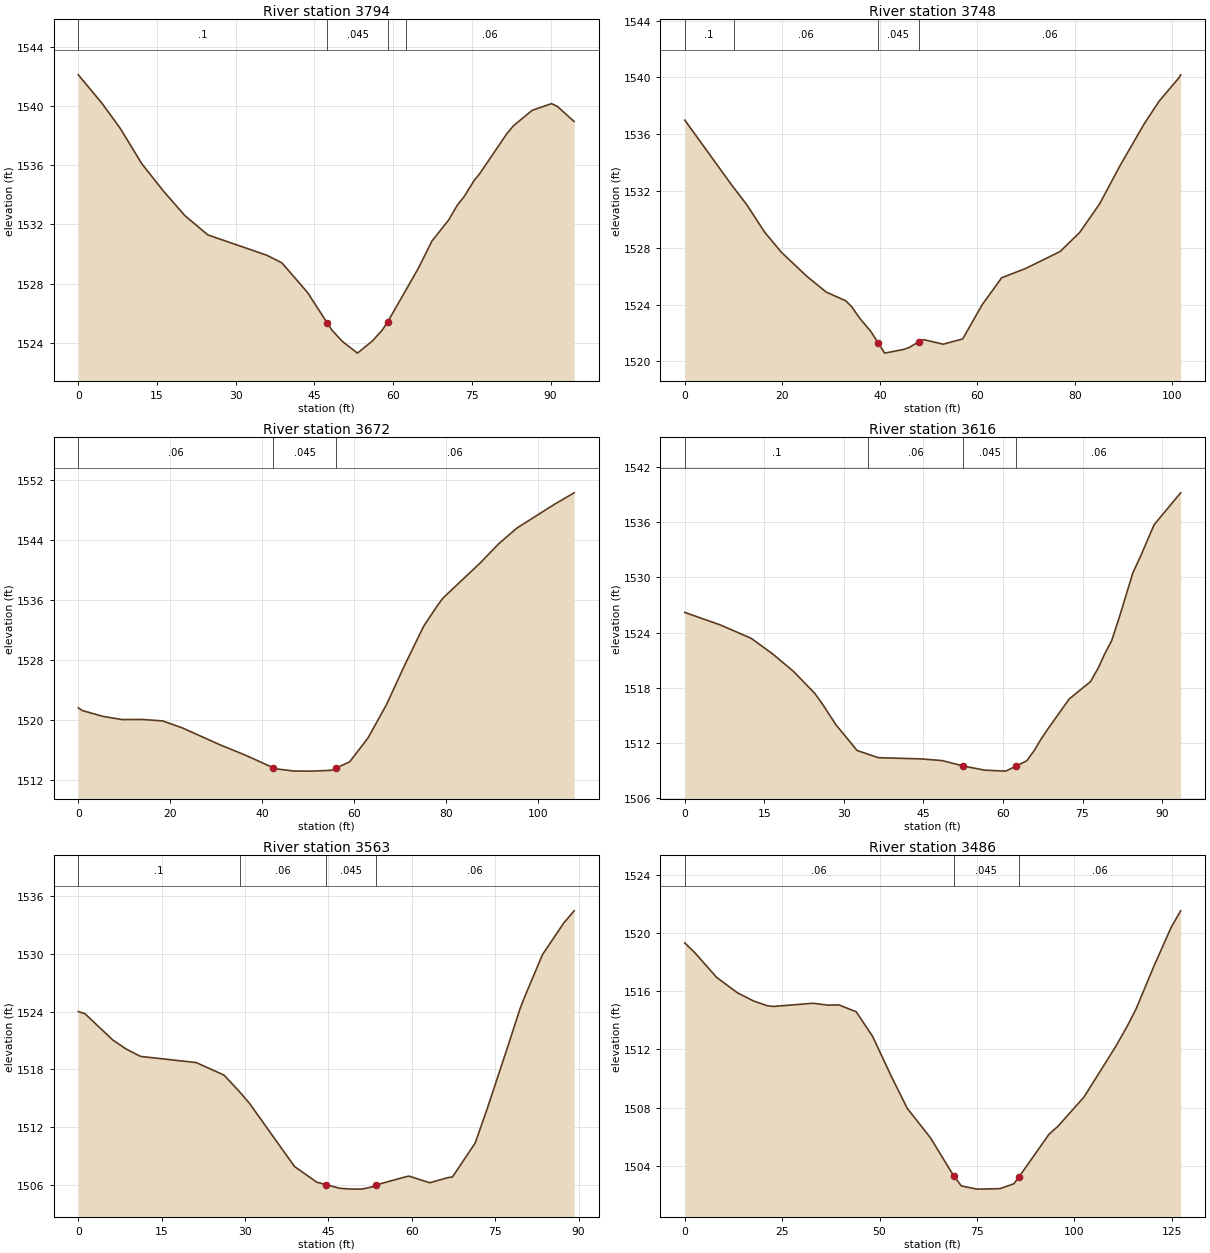
Type RM Length L Ch R = 1 ,3794    ,51.1,45.5,40
XS GIS Cut Line= 4
2152753.79836341648829.382865142 2152748.7602542648851.275601265
2152723.24602006648891.2605950532152709.80166678648911.907584757
#Sta/Elev= 30
       0 1542.13     4.5 1540.21       8  1538.5    12.1 1536.11    16.2 1534.27
    20.3  1532.6    24.7 1531.29    35.9 1529.92    38.8  1529.4    43.7 1527.39
    47.4 1525.35    48.4 1524.82    50.3 1524.09    53.2 1523.29    56.1 1524.13
    57.9 1524.84      59 1525.43    64.8 1529.03    67.4 1530.88    70.6 1532.31
    72.2 1533.29    73.5 1533.87    75.5 1535.01    76.4 1535.39    81.7 1538.16
    82.9 1538.67    86.5 1539.73    90.2 1540.18    91.3 1539.99    94.5 1538.97
#Mann= 4 ,-1,0
       0      .1       0    47.4    .045       0      59      .1       0
   62.46     .06       0
Bank Sta=47.4,59
XS Rating Curve= 0 ,0
Exp/Cntr(USF)=0,0
Exp/Cntr=0.3,0.1

Type RM Length L Ch R = 1 ,3748    ,76.2,76.5,77.2
XS GIS Cut Line= 4
2152695.44692915648820.8108440932152689.35397771648847.848316083
2152688.97316825648901.923260063 2152692.4880396648921.569220345
#Sta/Elev= 30
       0 1536.99     9.7 1532.38    12.7 1531.04    16.4 1529.09    19.8 1527.69
      25    1526      29 1524.88      33 1524.27    34.2 1523.86    35.9 1523.03
    38.2 1522.09    39.61521.328      41 1520.58      45 1520.85    46.1 1520.99
      48 1521.39      49 1521.53      53 1521.21      57 1521.58      61 1523.99
      65 1525.89    69.9 1526.54      77 1527.74      81 1529.08    85.1  1531.1
    89.2 1533.74    94.2 1536.71    97.3 1538.33   101.4 1539.99   101.7 1540.18
#Mann= 4 ,-1,0
       0      .1       0      10     .06       0    39.6    .045       0
      48     .06       0
Bank Sta=39.6,48
XS Rating Curve= 0 ,0
Exp/Cntr(USF)=0,0
Exp/Cntr=0.3,0.1

Type RM Length L Ch R = 1 ,3672    ,54.8,55.8,56.2
XS GIS Cut Line= 4
2152631.86689735 648848.306436662152621.96585127648871.916623468
2152625.39313645648914.5672835092152632.24770681648953.409848903
#Sta/Elev= 27
       0 1521.57      .9 1521.21     5.3 1520.44     9.5 1520.01      14 1520.02
    18.3 1519.83    22.6  1518.9    30.9 1516.61    36.3 1515.26    42.31513.596
    42.9 1513.43    46.9 1513.13    50.8 1513.12      55 1513.23    56.11513.543
      59 1514.37      63 1517.57      67 1522.01      71 1527.34    75.1  1532.5
      78 1535.17    79.2 1536.19    87.3 1540.89    91.4  1543.5    95.4 1545.61
   103.5 1548.76   107.8  1550.3
#Mann= 3 ,-1,0
       0     .06       0    42.3    .045       0    56.1     .06       0
Bank Sta=42.3,56.1
XS Rating Curve= 0 ,0
Exp/Cntr(USF)=0,0
Exp/Cntr=0.3,0.1

Type RM Length L Ch R = 1 ,3616    ,50.3,52.5,53.7
XS GIS Cut Line= 3
 2152570.2280298648844.6444987342152569.58312563648869.150857278
2152569.58312563648938.155603704
#Sta/Elev= 30
       0  1526.2     6.7 1524.84    12.5 1523.39    16.5 1521.72    20.5 1519.79
    24.5 1517.41      26 1516.21    28.5 1513.99    32.5 1511.19    36.5 1510.41
    44.5 1510.28    48.5  1510.1    52.5 1509.51    56.5 1509.06    60.5 1508.95
    62.51509.497    64.5 1510.08      66 1511.28    67.1 1512.36    68.5 1513.56
    72.5  1516.8    76.5 1518.67      78  1520.2    79.1  1521.6    80.5 1523.14
      82 1525.78    84.5 1530.51      86 1532.38    88.5 1535.73    93.5  1539.2
#Mann= 4 ,-1,0
       0      .1       0   34.51     .06       0    52.5    .045       0
    62.5     .06       0
Bank Sta=52.5,62.5
XS Rating Curve= 0 ,0
Exp/Cntr(USF)=0,0
Exp/Cntr=0.3,0.1

Type RM Length L Ch R = 1 ,3563    ,72.7,77,80.1
XS GIS Cut Line= 3
2152539.27262953648856.2527738332152521.86021688648879.469324033
2152511.54175013648938.800507876
#Sta/Elev= 30
       0 1524.01     1.2 1523.78     6.2 1521.05     8.6 1520.11    11.2 1519.34
    21.2  1518.7    26.2  1517.4      29 1515.67    30.8 1514.45    38.9 1507.88
    42.9 1506.25    44.61505.994      47 1505.62    49.2 1505.53    51.1 1505.54
    52.7 1505.74    53.6 1505.97    59.2 1506.86    59.6 1506.87    63.2 1506.19
    66.5 1506.73    67.3 1506.79    71.4 1510.33    73.5  1513.8    76.9 1519.73
    79.5 1524.36    80.4 1525.68    83.5 1529.93    87.3  1533.2    89.2 1534.49
#Mann= 4 ,-1,0
       0      .1       0   29.02     .06       0    44.6    .045       0
    53.6     .06       0
Bank Sta=44.6,53.6
XS Rating Curve= 0 ,0
Exp/Cntr(USF)=0,0
Exp/Cntr=0.3,0.1

Type RM Length L Ch R = 1 ,3486    ,65.4,68.8,71.7
XS GIS Cut Line= 3
2152494.12933748648820.1381401892152465.10864973648842.709786217
2152423.83478271648923.322807743
#Sta/Elev= 30
       0 1519.31     2.5 1518.66     8.2 1516.94    13.5 1515.89    17.7 1515.32
    21.2    1515    22.7 1514.95    32.9 1515.17    36.8 1515.04    39.5 1515.06
      44 1514.59    48.2 1512.91      53 1510.17    57.1 1507.97    63.1 1505.93
      69 1503.35      71 1502.64      75 1502.42    80.9 1502.45    84.5 1502.79
    85.71503.218    93.5 1506.18    95.8 1506.73   102.5 1508.74   110.6 1512.19
   113.6  1513.6   115.9  1514.8   120.4 1517.69   124.9 1520.39   127.3 1521.51
#Mann= 3 ,-1,0
       0     .06       0      69    .045       0    85.7     .06       0
Bank Sta=69,85.7
XS Rating Curve= 0 ,0
Exp/Cntr(USF)=0,0
Exp/Cntr=0.3,0.1

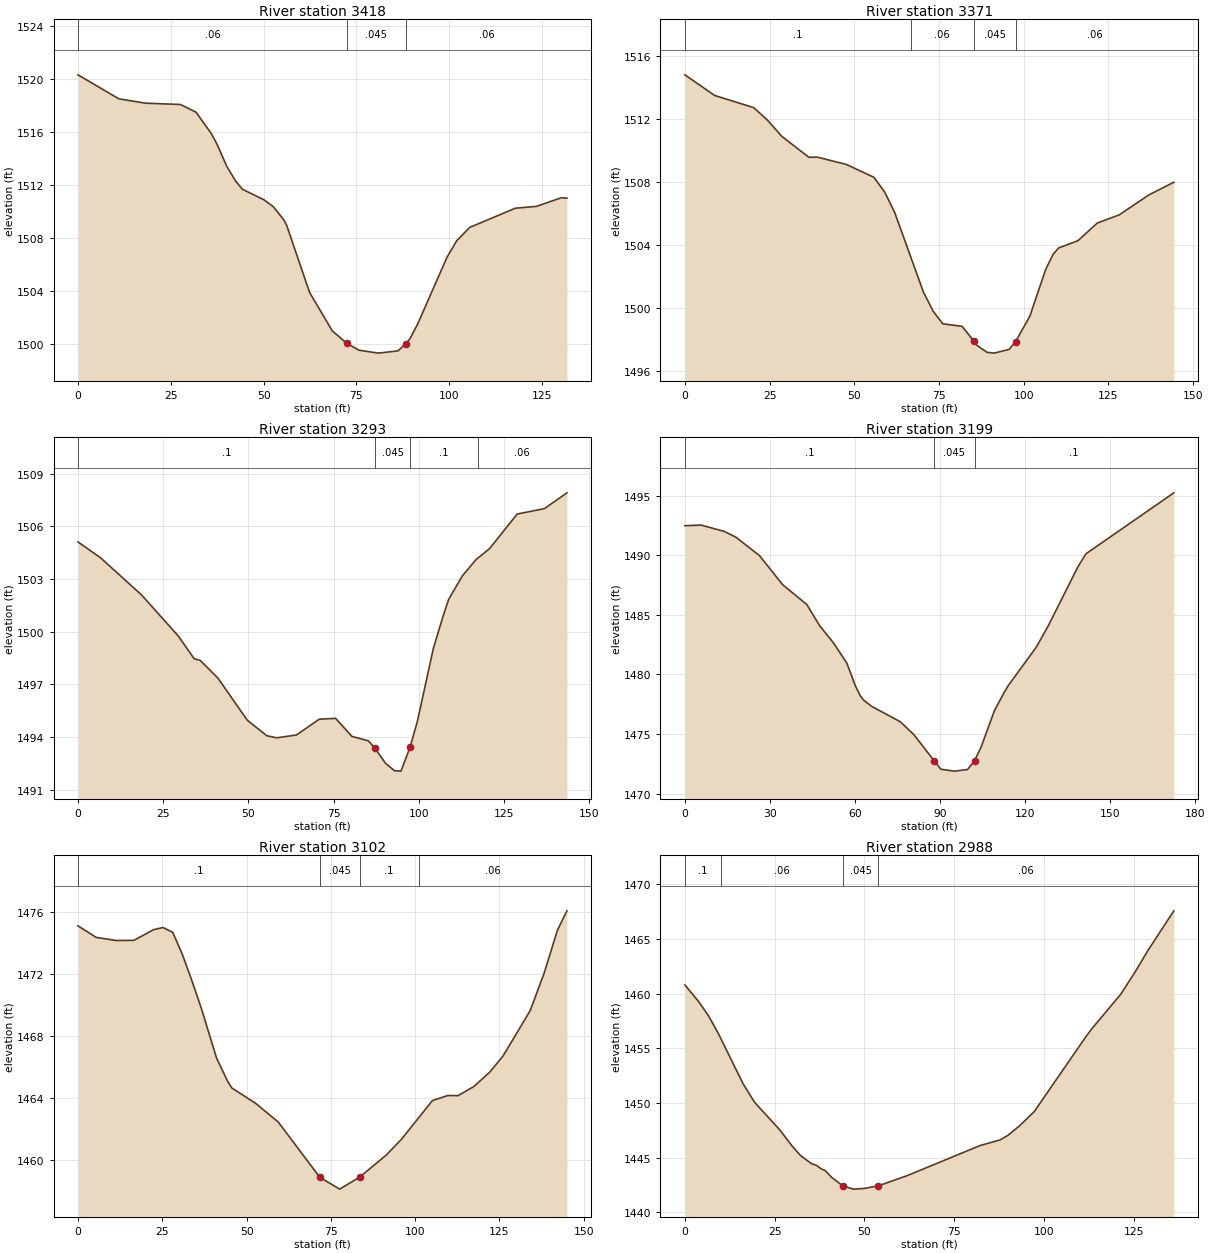
Type RM Length L Ch R = 1 ,3418    ,47.4,46.5,46.1
XS GIS Cut Line= 4
2152463.17393721 648796.921589992152448.98604542 648796.92158999
 2152419.3204535648805.9502484012152363.21379052648871.730473966
#Sta/Elev= 30
       0 1520.35      11 1518.54    18.2 1518.21    27.6 1518.11    31.8 1517.53
    35.9 1515.92    37.5 1515.08    40.1 1513.43    42.5 1512.31    44.3 1511.71
      50 1510.93    52.6  1510.4    55.4 1509.42    56.2    1509    62.4 1503.91
    68.5 1501.02    72.4 1500.08    75.7 1499.56    80.9 1499.34    86.2 1499.51
    88.31500.053    89.4 1500.42    91.5 1501.54    99.4 1506.58     102 1507.82
   105.5 1508.83   117.8 1510.28   123.5 1510.42   130.2 1511.07   131.7 1511.04
#Mann= 3 ,-1,0
       0     .06       0    72.4    .045       0    88.3     .06       0
Bank Sta=72.4,88.3
XS Rating Curve= 0 ,0
Exp/Cntr(USF)=0,0
Exp/Cntr=0.3,0.1

Type RM Length L Ch R = 1 ,3371    ,78,77.7,76.1
XS GIS Cut Line= 3
2152427.56495573648772.7437814592152392.53048498648762.081116449
2152326.26963813648847.001627066
#Sta/Elev= 30
       0  1514.8     8.8 1513.49    20.3 1512.72    24.4 1511.92    28.6  1510.9
    36.6 1509.57    39.1 1509.58    47.6 1509.12    55.8  1508.3      59 1507.35
    61.9 1506.08    70.4 1501.02    73.3  1499.8    76.1 1499.01    81.8 1498.85
    85.3 1497.91    86.2 1497.64    89.2  1497.2    91.3 1497.15    95.7 1497.39
    97.61497.883   101.8 1499.49   106.5 1502.47   108.7 1503.43   110.3 1503.82
     116 1504.28   121.7  1505.4   128.2 1505.92   136.9 1507.18   144.3 1507.99
#Mann= 4 ,-1,0
       0      .1       0   66.62     .06       0    85.3    .045       0
    97.6     .06       0
Bank Sta=85.3,97.6
XS Rating Curve= 0 ,0
Exp/Cntr(USF)=0,0
Exp/Cntr=0.3,0.1

Type RM Length L Ch R = 1 ,3293    ,93.7,94.1,92
XS GIS Cut Line= 6
2152366.66364828648719.3111649722152343.38558717648716.168917219
2152332.76100311648715.8261887012152320.09065075 648731.07817743
2152290.76832197648775.6328847942152289.24508411648811.809783936
#Sta/Elev= 30
       0 1505.12     6.6 1504.22    18.7 1502.09    29.5 1499.74    34.1 1498.46
    35.9 1498.36    41.1 1497.35    49.7 1494.95    55.4 1494.07    58.3 1493.95
    64.1 1494.11    70.8 1495.01    75.6 1495.06    80.4 1494.03    85.2 1493.78
    87.2 1493.35    90.2 1492.51    92.9 1492.07    94.8 1492.05    97.5 1493.44
    99.6 1494.88   104.3 1499.05   107.3 1500.98   108.8 1501.85   112.8 1503.18
   116.8 1504.11   120.8 1504.74   128.9 1506.71   136.9 1507.02   143.5 1507.92
#Mann= 4 ,-1,0
       0      .1       0    87.2    .045       0    97.5      .1       0
  117.29     .06       0
Bank Sta=87.2,97.5
XS Rating Curve= 0 ,0
Exp/Cntr(USF)=0,0
Exp/Cntr=0.3,0.1

Type RM Length L Ch R = 1 ,3199    ,97.1,97.2,94.7
XS GIS Cut Line= 5
2152305.74031907648643.4007939142152263.89829147648653.273631886
2152219.70558816648722.8536328342152210.77302047648739.308362788
2152213.59383132648767.516471281
#Sta/Elev= 30
       0  1492.5     5.7 1492.55    13.9 1492.02      18 1491.53    26.3 1489.99
    34.5 1487.54      43 1485.88    47.6 1484.08    52.4 1482.66    57.1 1480.97
    60.1 1479.07    61.8 1478.24      63 1477.86    65.9 1477.32      76 1476.03
    80.8 1474.94    87.91472.763    90.3 1472.04      95 1471.88    99.7 1472.01
   102.2 1472.76   104.5  1473.9   109.2 1476.96   112.3 1478.34     114 1479.04
   123.9 1482.27   128.1 1484.04   138.6 1489.02   141.5 1490.14   172.5 1495.26
#Mann= 3 ,-1,0
       0      .1       0    87.9    .045       0   102.2      .1       0
Bank Sta=87.9,102.2
XS Rating Curve= 0 ,0
Exp/Cntr(USF)=0,0
Exp/Cntr=0.3,0.1

Type RM Length L Ch R = 1 ,3102    ,111.9,113.6,112.9
XS GIS Cut Line= 4
2152196.68397657648606.1018383432152165.79609777648633.181622496
2152131.10012433 648695.803623352152134.06197572648727.960867031
#Sta/Elev= 30
       0 1475.13     5.4 1474.38    11.3 1474.18    16.6 1474.19    22.4 1474.88
    25.2 1475.02    28.1 1474.71    30.9 1473.31    33.7 1471.63    36.6 1469.78
    41.1 1466.57    44.4 1465.06    45.6 1464.64    52.7 1463.64    59.4 1462.43
    71.7 1458.86    77.6 1458.09    83.5 1458.86    91.4 1460.29    95.9 1461.31
   105.1 1463.82   109.7 1464.15   112.7 1464.14   117.4 1464.73   122.1 1465.66
   126.1 1466.72   134.1 1469.64   138.2 1472.04   142.2 1474.85     145  1476.1
#Mann= 4 ,-1,0
       0      .1       0    71.7    .045       0    83.5      .1       0
  101.08     .06       0
Bank Sta=71.7,83.5
XS Rating Curve= 0 ,0
Exp/Cntr(USF)=0,0
Exp/Cntr=0.3,0.1

Type RM Length L Ch R = 1 ,2988    ,70.4,63.2,58.3
XS GIS Cut Line= 4
2152087.09547508648582.830148837 2152068.9012451648602.716865324
2152039.11034829648655.7272143952152044.36019071 648703.84293427
#Sta/Elev= 30
       0 1460.78     3.7 1459.32     6.6 1457.96     9.4 1456.29    16.2 1451.76
    19.4 1450.06    26.4 1447.55    29.8 1446.09    32.2 1445.19    35.2 1444.46
    36.6  1444.3    38.1 1443.95      39 1443.84      41 1443.16      44 1442.42
    46.9 1442.12    49.9 1442.18    53.81442.413    61.9 1443.35    82.2  1446.1
    87.8 1446.62      90 1447.04    93.2  1447.9    97.3  1449.2   111.8  1456.1
   113.4  1456.8   121.4 1459.93   125.4 1461.96   128.8 1463.84   136.2 1467.56
#Mann= 4 ,-1,0
       0      .1       0      10     .06       0      44    .045       0
    53.8     .06       0
Bank Sta=44,53.8
XS Rating Curve= 0 ,0
Exp/Cntr(USF)=0,0
Exp/Cntr=0.3,0.1

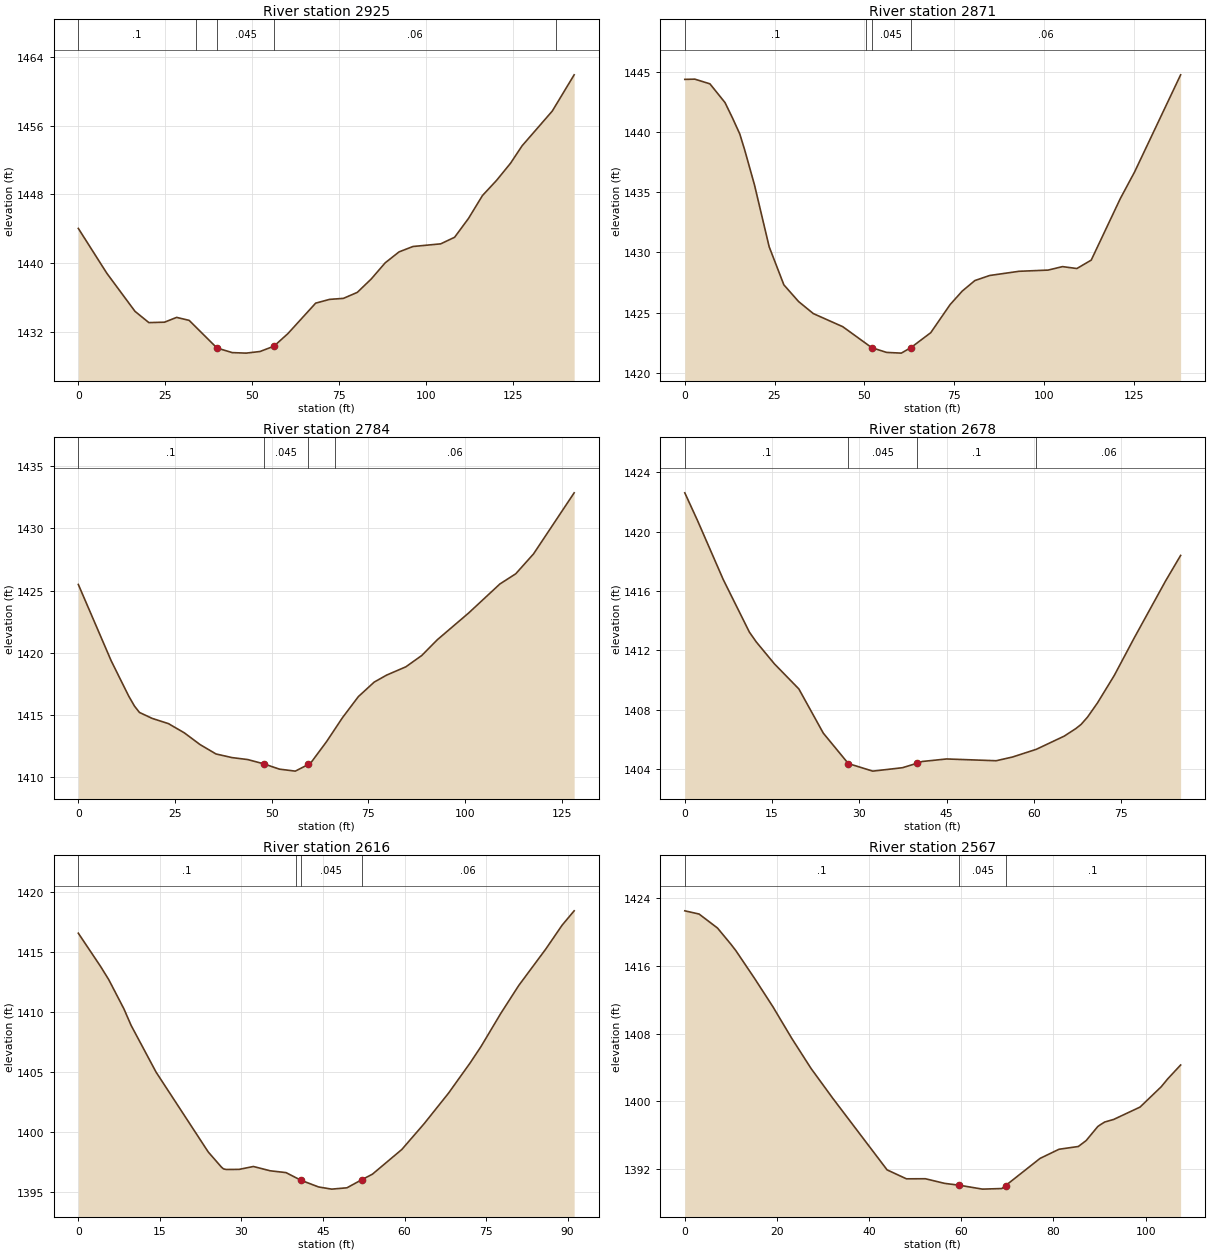
Type RM Length L Ch R = 1 ,2925    ,50.5,54.3,56
XS GIS Cut Line= 4
2152003.94692681648553.0673770222152000.65598082648576.574134099
2152000.65598082648630.169540235 2151999.2455754648695.518324909
#Sta/Elev= 30
       0 1444.03     8.2  1438.8    16.3 1434.36    20.3 1433.04    24.8 1433.09
    28.3 1433.65    31.9  1433.3    39.9 1430.08    44.3 1429.54    48.3 1429.48
    52.3 1429.67    56.3 1430.29    60.3 1431.75    68.3 1435.31    72.3 1435.75
    76.3 1435.87    80.3 1436.57    84.3 1438.13    88.3 1440.01    92.3 1441.29
    96.3 1441.92   104.3 1442.23   108.3    1443   112.3  1445.2   116.3 1447.86
   120.4 1449.65   124.4 1451.64   127.7 1453.66   136.4 1457.72   142.7 1461.95
#Mann= 5 ,-1,0
       0      .1       0   33.74     .06       0    39.9    .045       0
    56.3     .06       0  137.33      .1       0
Bank Sta=39.9,56.3
XS Rating Curve= 0 ,0
Exp/Cntr(USF)=0,0
Exp/Cntr=0.3,0.1

Type RM Length L Ch R = 1 ,2871    ,87.6,87.1,87.3
XS GIS Cut Line= 4
2151962.10489921648538.4931876342151958.81395322648548.366025607
2151940.94881785 648631.579945662151945.65016926648673.892108398
#Sta/Elev= 30
       0  1444.4     2.8 1444.42       7 1444.03    11.2 1442.47    13.3 1441.18
    15.3 1439.87    16.7 1438.51    19.4 1435.63    23.5 1430.47    27.6  1427.3
    31.7 1425.91    35.8 1424.91      44 1423.82    52.1 1422.07    56.2 1421.68
    60.3 1421.62      631422.082    68.5 1423.32    73.9 1425.66    77.3 1426.79
    80.8 1427.66    84.9 1428.08    93.1 1428.43   101.2 1428.53   105.2 1428.82
   109.2 1428.66   113.2 1429.36   121.3 1434.48   125.3 1436.71   138.1 1444.78
#Mann= 4 ,-1,0
       0      .1       0   50.41     .06       0    52.1    .045       0
      63     .06       0
Bank Sta=52.1,63
XS Rating Curve= 0 ,0
Exp/Cntr(USF)=0,0
Exp/Cntr=0.3,0.1

Type RM Length L Ch R = 1 ,2784    ,99.3,106.2,119.2
XS GIS Cut Line= 4
2151884.80695812648531.4775736822151872.53643092648542.478735994
2151857.72717397648611.8706828862151850.95722793648652.067237488
#Sta/Elev= 30
       0 1425.49     8.5 1419.35      13 1416.53    14.5 1415.72    15.8  1415.2
    19.1 1414.72    23.3  1414.3    27.4 1413.56    31.5 1412.61    35.6 1411.86
    39.7 1411.57    43.8 1411.41    47.9 1411.07      52 1410.64    56.1 1410.48
    59.5 1411.02    60.1 1411.14    64.2 1412.86    68.3 1414.78    72.4 1416.47
    76.5 1417.64    79.7  1418.2    84.7 1418.87    88.8 1419.78    92.8 1421.04
   100.9 1423.19     109 1425.53   113.1 1426.35   117.7 1427.95   128.2 1432.86
#Mann= 4 ,-1,0
       0      .1       0    47.9    .045       0    59.5      .1       0
   66.48     .06       0
Bank Sta=47.9,59.5
XS Rating Curve= 0 ,0
Exp/Cntr(USF)=0,0
Exp/Cntr=0.3,0.1

Type RM Length L Ch R = 1 ,2678    ,64.9,61.5,55.8
XS GIS Cut Line= 4
2151862.15203345648510.7773187462151851.80347118648515.822073468
 2151805.6832138648531.9006953092151785.79649731648546.709952268
#Sta/Elev= 26
       0 1422.62     2.2 1420.74     6.6 1416.78    11.1 1413.23    12.3 1412.56
    15.4 1411.09    19.6  1409.4    23.8 1406.42    28.1 1404.37    32.3 1403.86
    37.4 1404.09    39.9 1404.39    40.8 1404.51      45 1404.68    53.5 1404.56
    56.3 1404.81    60.4 1405.33    65.2 1406.22    67.2 1406.73    68.1 1407.01
    69.2  1407.5    70.9 1408.45    73.8 1410.31    77.2 1412.82    82.6 1416.67
    85.2  1418.4
#Mann= 4 ,-1,0
       0      .1       0    28.1    .045       0    39.9      .1       0
   60.36     .06       0
Bank Sta=28.1,39.9
XS Rating Curve= 0 ,0
Exp/Cntr(USF)=0,0
Exp/Cntr=0.3,0.1

Type RM Length L Ch R = 1 ,2616    ,44.1,48.8,53.7
XS GIS Cut Line= 2
2151816.34636699648463.5836017922151748.60950266648524.657823732
#Sta/Elev= 30
       0 1416.57     4.1 1413.79     5.6 1412.69     8.4 1410.24     9.7 1408.88
    14.3 1404.97    23.9  1398.3    26.3 1397.05    26.7 1396.89    27.2 1396.84
    29.6 1396.85    32.2 1397.09    35.3 1396.73    38.2 1396.58    40.9 1395.95
    44.2 1395.38    46.6  1395.2    49.4 1395.31    52.2    1396    54.1 1396.45
    59.5 1398.51    63.6 1400.66    68.1 1403.22    72.1 1405.76    74.1 1407.13
    77.7 1409.87      81  1412.2      86 1415.26      89 1417.25    91.2 1418.44
#Mann= 4 ,-1,0
       0      .1       0      40     .06       0    40.9    .045       0
    52.2     .06       0
Bank Sta=40.9,52.2
XS Rating Curve= 0 ,0
Exp/Cntr(USF)=0,0
Exp/Cntr=0.3,0.1

Type RM Length L Ch R = 1 ,2567    ,47.5,42.8,36.6
XS GIS Cut Line= 4
2151819.29603248648442.440552569 2151798.7528851648442.162942469
2151733.79212176648459.6523787522151724.07576827648476.864204935
#Sta/Elev= 30
       0 1422.54     3.1 1422.16     7.1  1420.5      10 1418.59    11.1 1417.81
    15.1 1414.57    19.1  1411.2    23.2 1407.45    27.4 1403.87    32.1 1400.35
    43.9 1391.86    48.1  1390.8    52.2 1390.81    56.4 1390.26    59.6 1390.04
    64.6 1389.58    68.8 1389.65    69.6 1389.99    77.1 1393.22    81.2  1394.3
    85.4 1394.63    87.1 1395.33    89.6 1396.98    90.1 1397.18    91.1 1397.52
    93.1 1397.84    98.8  1399.3   103.4 1401.71   104.8 1402.64   107.6 1404.28
#Mann= 3 ,-1,0
       0      .1       0    59.6    .045       0    69.6      .1       0
Bank Sta=59.6,69.6
XS Rating Curve= 0 ,0
Exp/Cntr(USF)=0,0
Exp/Cntr=0.3,0.1

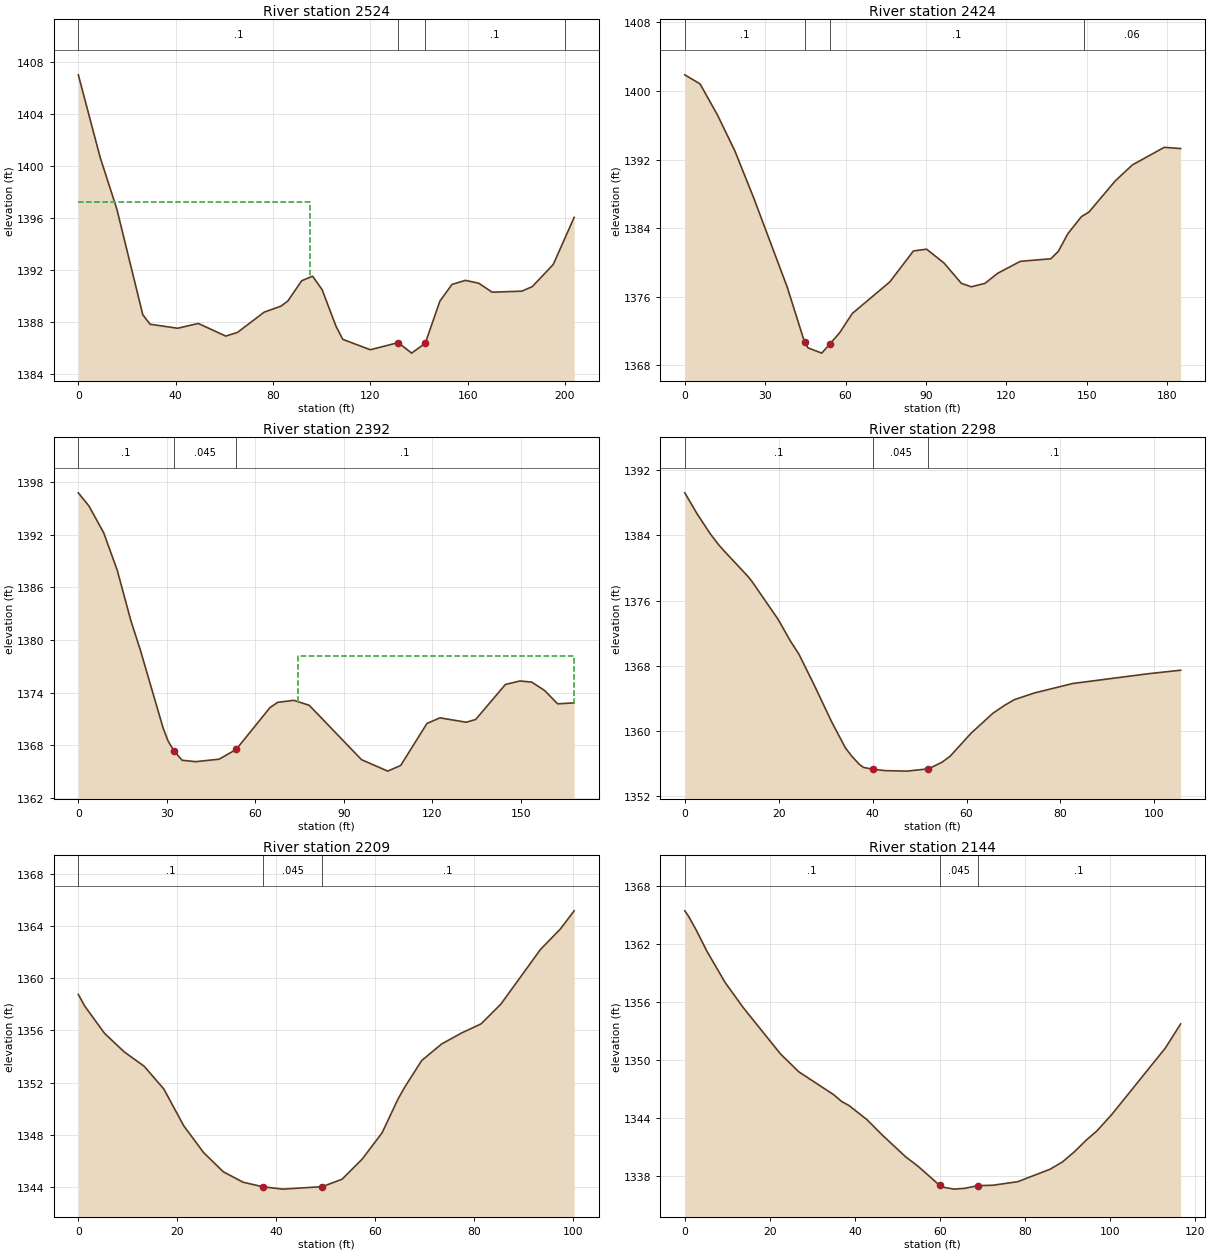
Type RM Length L Ch R = 1 ,2524    ,85.2,100.6,84
XS GIS Cut Line= 2
2151851.67835616648318.9718268142151703.71154288648459.109503435
#Sta/Elev= 30
       0 1407.01       9 1400.65    15.8 1396.72    26.5 1388.58    29.5 1387.85
    40.8 1387.54    49.3 1387.91    60.6 1386.94    65.4 1387.22    76.4 1388.78
    83.3 1389.24    86.1 1389.63    91.8 1391.19    96.3 1391.54   100.2 1390.51
   105.9  1387.7   108.7 1386.69     120 1385.89   131.5 1386.44     137 1385.63
   142.6 1386.39   148.6 1389.62   153.6 1390.91   159.1 1391.22   164.6    1391
   170.1 1390.31   182.3 1390.39   186.6 1390.74   195.2 1392.44   203.8 1396.06
#Mann= 4 ,-1,0
       0      .1       0   131.5    .045       0   142.6      .1       0
     200     .06       0
#XS Ineff= 2 , 0
           95.41 1397.27
Permanent Ineff=
       F       F
Bank Sta=131.5,142.6
XS Rating Curve= 0 ,0
Exp/Cntr(USF)=0,0
Exp/Cntr=0.3,0.1

Type RM Length L Ch R = 1 ,2424    ,45.2,32.1,54.5
XS GIS Cut Line= 3
2151759.67822757648276.8930886362151692.72647352648362.659560348
2151644.81376504648421.959032655
#Sta/Elev= 30
       0 1401.89     5.7 1400.83    12.2  1397.2    18.7    1393    25.7 1387.54
    38.2 1377.14    44.7 1370.69      46 1370.03    51.1 1369.42      54 1370.45
    57.7 1371.76    62.5 1374.05    76.5 1377.73    85.3 1381.34    90.2 1381.55
    96.7 1379.94   103.2 1377.56   106.9 1377.16     112 1377.56   116.7 1378.73
   125.2 1380.13   136.6 1380.43   139.4 1381.31   142.9 1383.34     148 1385.35
   150.8 1385.88   160.6 1389.51     167 1391.38   178.9 1393.43     185 1393.29
#Mann= 4 ,-1,0
       0      .1       0    44.7    .045       0      54      .1       0
   148.8     .06       0
Bank Sta=44.7,54
XS Rating Curve= 0 ,0
Exp/Cntr(USF)=0,0
Exp/Cntr=0.3,0.1

Type RM Length L Ch R = 1 ,2392    ,87.7,93.6,75.3
XS GIS Cut Line= 4
2151747.58039466648263.6853013662151731.35489759648273.086470698
2151689.56510723648313.3091439192151607.10558148 648352.70852465
#Sta/Elev= 30
       0 1396.79     3.6 1395.29     8.6 1392.23    13.2 1387.95    17.8 1382.22
    21.1 1378.77    28.7    1370    30.4 1368.49    32.4 1367.35    35.2 1366.27
    39.8 1366.11    47.7 1366.39    53.5  1367.5      65 1372.29    67.6 1372.88
    73.1 1373.11    78.3 1372.54      96 1366.34   104.9 1365.03   109.3 1365.68
   118.2 1370.47   122.6 1371.11   131.5 1370.61   134.7 1370.92   144.8 1374.92
   149.7 1375.32   153.7 1375.19   158.1 1374.23   162.5 1372.71   168.1 1372.82
#Mann= 3 ,-1,0
       0      .1       0    32.4    .045       0    53.5      .1       0
#XS Ineff= 2 , 0
                           74.64         1378.18
Permanent Ineff=
       F       F
Bank Sta=32.4,53.5
XS Rating Curve= 0 ,0
Exp/Cntr(USF)=0,0
Exp/Cntr=0.3,0.1

Type RM Length L Ch R = 1 ,2298    ,93,89.4,80.6
XS GIS Cut Line= 4
2151660.59218849 648213.994357542151646.85048855648231.233944733
2151622.11542866 648274.957535442151617.61814505648307.937615288
#Sta/Elev= 30
       0 1389.19     2.6 1386.64     5.4 1384.19     7.1 1382.91     8.3 1382.12
    13.5 1378.92    14.3 1378.34    19.9 1373.67    22.5 1371.03    24.3 1369.43
    27.5 1365.72    31.3 1361.11    34.2 1357.96    35.6  1356.9    37.2 1355.92
    38.1 1355.55    40.1 1355.33    42.7 1355.16    47.3  1355.1    51.9 1355.38
    54.8  1356.2    56.5 1356.92      61 1359.76    65.6 1362.18    68.1 1363.16
    70.2 1363.86    74.5 1364.68    82.6 1365.83    98.7 1367.03   105.6 1367.46
#Mann= 3 ,-1,0
       0      .1       0    40.1    .045       0    51.9      .1       0
Bank Sta=40.1,51.9
XS Rating Curve= 0 ,0
Exp/Cntr(USF)=0,0
Exp/Cntr=0.3,0.1

Type RM Length L Ch R = 1 ,2209    ,55.9,65.1,71.8
XS GIS Cut Line= 5
2151552.02670919648199.9138708862151552.25157338648214.530042637
2151555.84940027648270.7460878322151557.19858535648291.433592463
2151556.74885699648299.978431333
#Sta/Elev= 26
       0 1358.76     1.3 1357.86     5.3 1355.77     9.3 1354.34    13.3 1353.25
    17.3 1351.49    21.3 1348.68    25.3 1346.63    29.3 1345.15    33.3 1344.35
    37.3    1344    41.3 1343.82    49.3 1344.01    53.3 1344.58    57.4 1346.14
    61.4 1348.15    64.6 1350.73      66 1351.67    69.4 1353.69    73.4 1354.95
    77.4 1355.79    81.4  1356.5    85.4 1358.02    93.4 1362.21    97.4 1363.77
   100.2 1365.17
#Mann= 3 ,-1,0
       0      .1       0    37.3    .045       0    49.3      .1       0
Bank Sta=37.3,49.3
XS Rating Curve= 0 ,0
Exp/Cntr(USF)=0,0
Exp/Cntr=0.3,0.1

Type RM Length L Ch R = 1 ,2144    ,54.7,62.3,56.1
XS GIS Cut Line= 4
2151533.17449843648192.3198173712151521.63896596648221.259837437
2151473.27068067648265.7829452312151467.60410331648284.604077162
#Sta/Elev= 30
       0 1365.43      .9 1364.86     2.7 1363.43     5.2 1361.25     9.5    1358
    13.8 1355.38    22.5 1350.62    26.8 1348.77      35  1346.4    36.9 1345.69
    38.6 1345.28    42.8 1343.83    46.3 1342.28    51.9 1339.98    54.9 1338.97
    59.91337.024    60.4 1336.85    63.3 1336.62    65.8  1336.7    68.9 1336.98
    72.4 1337.02    78.3 1337.39    85.9 1338.68    88.8 1339.43    91.6 1340.48
    94.4 1341.69    96.9 1342.64   100.4 1344.34     113 1351.22   116.6 1353.72
#Mann= 3 ,-1,0
       0      .1       0    59.9    .045       0    68.9      .1       0
Bank Sta=59.9,68.9
XS Rating Curve= 0 ,0
Exp/Cntr(USF)=0,0
Exp/Cntr=0.3,0.1