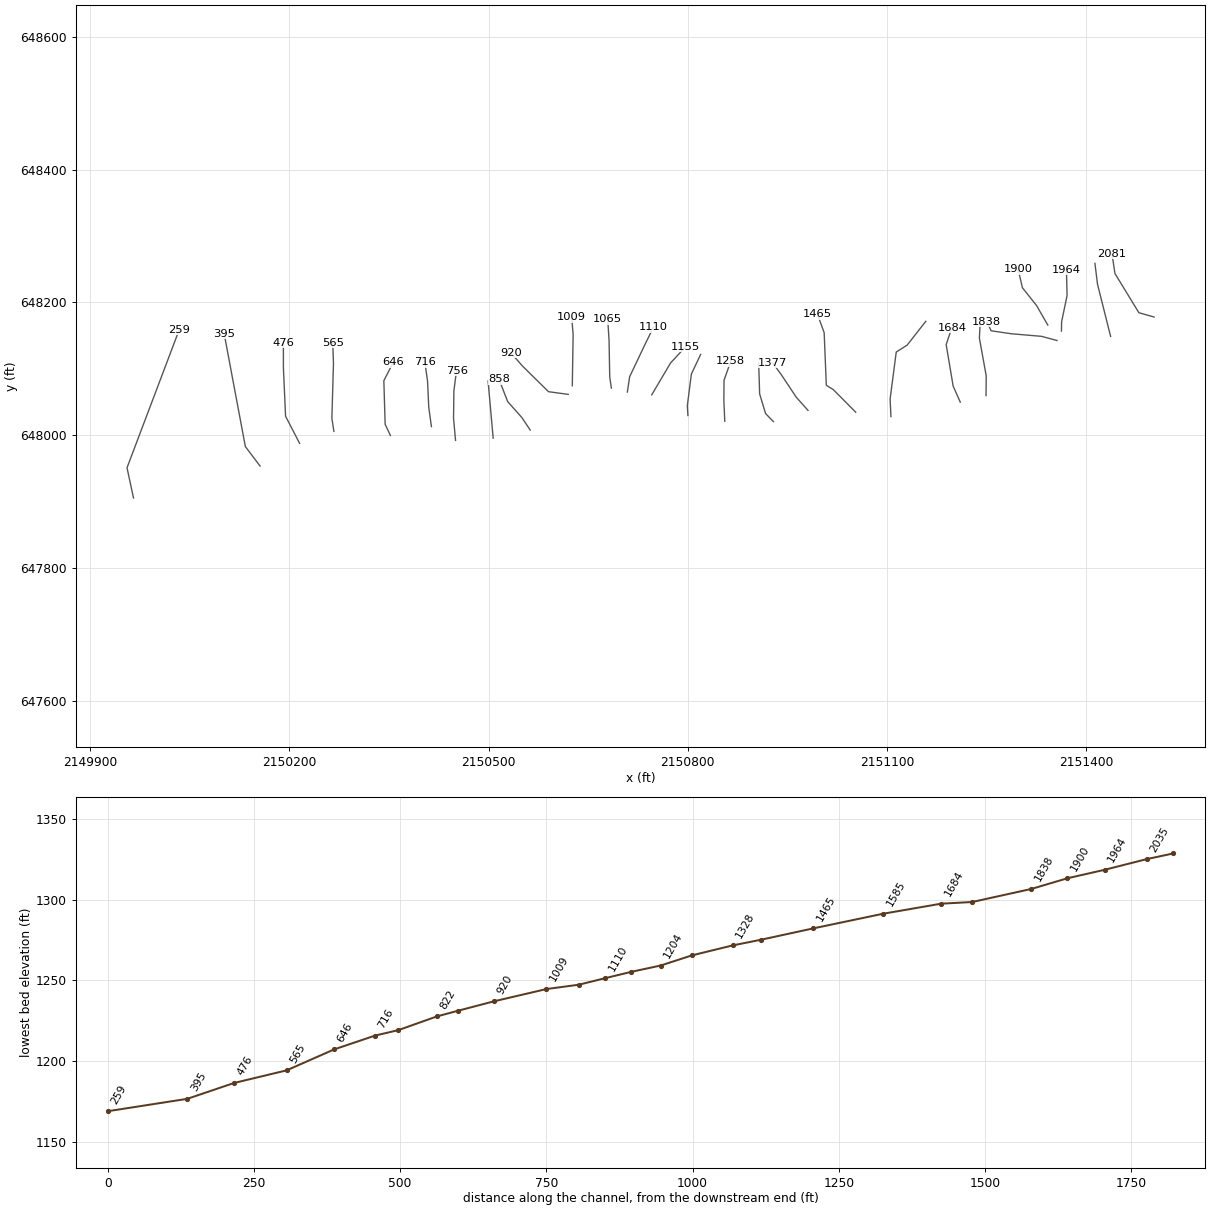
HEC-RAS study LYNNCMPRN.prj: LYNNCMPRN

--- LYNNCMPRN.g01 (geometry) --- (continued)

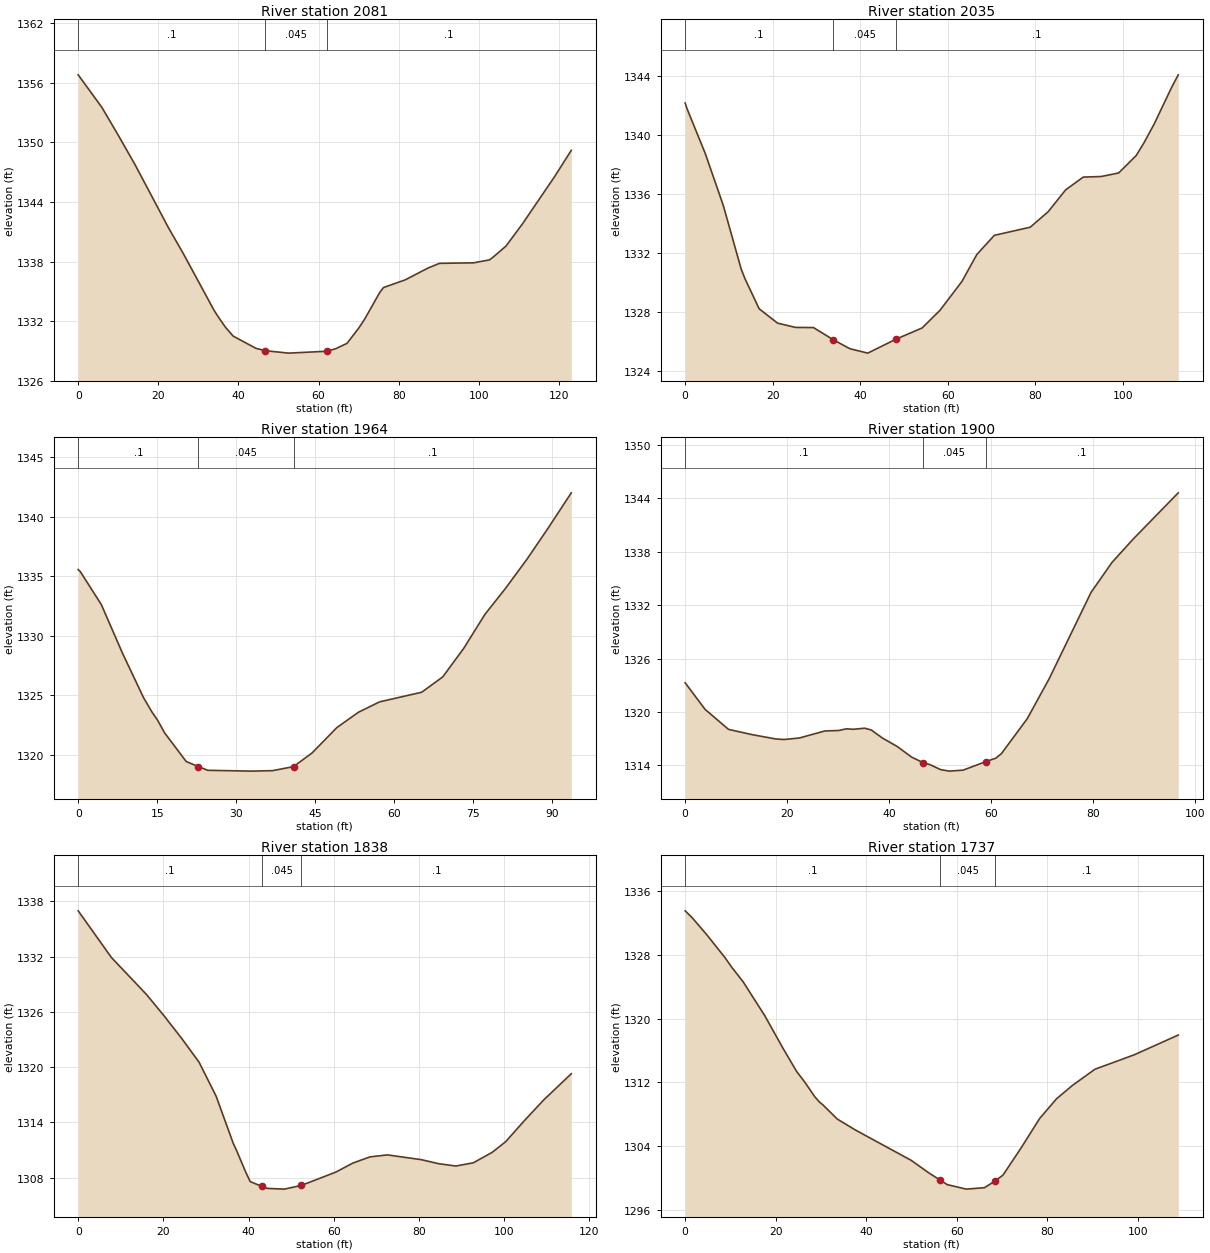
Type RM Length L Ch R = 1 ,2081    ,47.1,45.9,40.6
XS GIS Cut Line= 4
2151501.80594521648177.9509962192151478.93725803648184.427084626
2151442.91401626648243.5213913342151438.46170549648273.270922451
#Sta/Elev= 30
       0  1356.8     5.9 1353.53      10 1350.72    14.2 1347.75    22.5 1341.43
    26.3 1338.76      34 1333.03    35.1 1332.35    36.8 1331.37    38.7 1330.49
    44.4 1329.26    46.7 1329.03    52.5 1328.78    62.1 1328.97    64.2 1329.21
    67.1 1329.76      70 1331.28    71.5 1332.19    75.2 1334.83    76.2 1335.38
    81.6 1336.15    87.4 1337.36    90.2 1337.82    98.7 1337.87   102.7 1338.17
   103.9 1338.55   106.8 1339.56   110.9 1341.79   118.9 1346.53   123.1  1349.2
#Mann= 3 ,-1,0
       0      .1       0    46.7    .045       0    62.1      .1       0
Bank Sta=46.7,62.1
XS Rating Curve= 0 ,0
Exp/Cntr(USF)=0,0
Exp/Cntr=0.3,0.1

Type RM Length L Ch R = 1 ,2035    ,70.9,71.7,62.5
XS GIS Cut Line= 3
2151436.42052982648148.7553406632151416.63248191648227.457803936
2151412.80979083648258.713925064
#Sta/Elev= 30
       0 1342.14      .4 1341.78     4.6 1338.72     8.7 1335.22    12.8  1330.9
    13.7 1330.23    16.9 1328.22    21.1 1327.25    25.2 1326.96    29.3 1326.95
    33.8 1326.13    37.6 1325.52    41.7 1325.22    48.11326.159    54.1 1326.92
    58.2 1328.12    63.2 1330.07    66.6 1331.89    70.6 1333.19    78.8 1333.74
    82.9 1334.79    86.9 1336.27    90.9 1337.13      95 1337.17      99 1337.41
     103 1338.59   104.7 1339.41   107.1 1340.72   111.1 1343.21   112.6 1344.05
#Mann= 3 ,-1,0
       0      .1       0    33.8    .045       0    48.1      .1       0
Bank Sta=33.8,48.1
XS Rating Curve= 0 ,0
Exp/Cntr(USF)=0,0
Exp/Cntr=0.3,0.1

Type RM Length L Ch R = 1 ,1964    ,47.7,63.7,70
XS GIS Cut Line= 4
2151362.36525961648156.803257455 2151362.6151087648170.794806481
2151370.86012867648210.2709626622151369.86073231648249.497269753
#Sta/Elev= 27
       0 1335.55      .4 1335.38     4.4  1332.6     8.4 1328.53    12.4 1324.79
      14 1323.58    15.1 1322.87    16.4 1321.83    20.5 1319.42    22.81318.992
    24.6 1318.68    32.8 1318.61    36.9 1318.65    40.9 1318.99    40.9    1319
    44.4 1320.14    49.1 1322.27    53.2 1323.56    57.2 1324.43    65.2 1325.24
    69.2 1326.53    73.2 1328.94    77.2 1331.78    81.2 1334.02    85.2 1336.43
    89.2 1339.03    93.6    1342
#Mann= 3 ,-1,0
       0      .1       0    22.8    .045       0    40.9      .1       0
Bank Sta=22.8,40.9
XS Rating Curve= 0 ,0
Exp/Cntr(USF)=0,0
Exp/Cntr=0.3,0.1

Type RM Length L Ch R = 1 ,1900    ,51.9,61.6,69.2
XS GIS Cut Line= 4
2151341.87763425648165.7978246862151324.88789615648195.280017277
2151303.65072352 648222.013869882151297.15464719648249.747118843
#Sta/Elev= 30
       0 1323.28     3.9  1320.3     8.5 1318.05    13.1 1317.46    17.8 1316.97
    19.4 1316.91    22.4 1317.08    27.4 1317.87    30.1 1317.92    31.6 1318.11
      33 1318.06    35.2 1318.18    36.5 1317.98    38.7 1317.07    41.6 1316.12
    44.4 1314.94    46.7  1314.3      48 1314.09    50.1 1313.53    51.8 1313.36
    54.5 1313.47    58.91314.414    60.9 1314.81      62 1315.31    67.1 1319.26
    71.4 1323.75    79.6 1333.43    83.7 1336.79    87.9 1339.44    96.7 1344.61
#Mann= 3 ,-1,0
       0      .1       0    46.7    .045       0    58.9      .1       0
Bank Sta=46.7,58.9
XS Rating Curve= 0 ,0
Exp/Cntr(USF)=0,0
Exp/Cntr=0.3,0.1

Type RM Length L Ch R = 1 ,1838    ,112,101.2,84.9
XS GIS Cut Line= 5
2151355.69790233648142.6146657172151332.22208185648148.888376361
2151287.09184077648152.7335538532151256.56749986648157.225007656
2151249.92512301648171.025838543
#Sta/Elev= 28
       0 1336.98     7.8 1331.91    16.1 1327.86    20.2 1325.55    24.3 1323.12
    28.4 1320.52    32.4 1316.83    36.4 1311.73    37.2 1310.93    39.4 1308.53
    40.4 1307.56    43.1 1307.04    44.4 1306.82    48.4 1306.74    52.4 1307.14
    60.5 1308.59    64.5 1309.57    68.5 1310.24    72.6 1310.46    80.6 1309.94
    84.7  1309.5    88.7 1309.25    92.8  1309.6    97.2 1310.73   100.4  1311.9
   104.8 1314.19   109.3 1316.42   115.8 1319.28
#Mann= 3 ,-1,0
       0      .1       0    43.1    .045       0    52.4      .1       0
Bank Sta=43.1,52.4
XS Rating Curve= 0 ,0
Exp/Cntr(USF)=0,0
Exp/Cntr=0.3,0.1

Type RM Length L Ch R = 1 ,1737    ,52.7,53.1,52.5
XS GIS Cut Line= 4
2151248.84882865648059.6294805912151249.12643875648089.333761262
2151238.85486506648146.2438317062151239.96530546648167.619809384
#Sta/Elev= 30
       0 1333.48     1.5 1332.65     4.8 1330.47     8.8 1327.62    10.3 1326.41
    12.8  1324.6    17.6 1320.34    21.6 1316.28    24.6 1313.39    26.5 1311.97
    28.6 1310.23    29.6 1309.57    30.4  1309.2    33.6 1307.41    37.7 1306.01
    49.9 1302.25    53.9 1300.64    56.31299.776    57.9  1299.2    62.1 1298.64
    66.1 1298.82    68.51299.675    70.2  1300.4    74.3 1303.89    78.3 1307.49
      82 1309.94    85.5 1311.61    90.5 1313.65    99.2 1315.46   108.9 1317.93
#Mann= 3 ,-1,0
       0      .1       0    56.3    .045       0    68.5      .1       0
Bank Sta=56.3,68.5
XS Rating Curve= 0 ,0
Exp/Cntr(USF)=0,0
Exp/Cntr=0.3,0.1

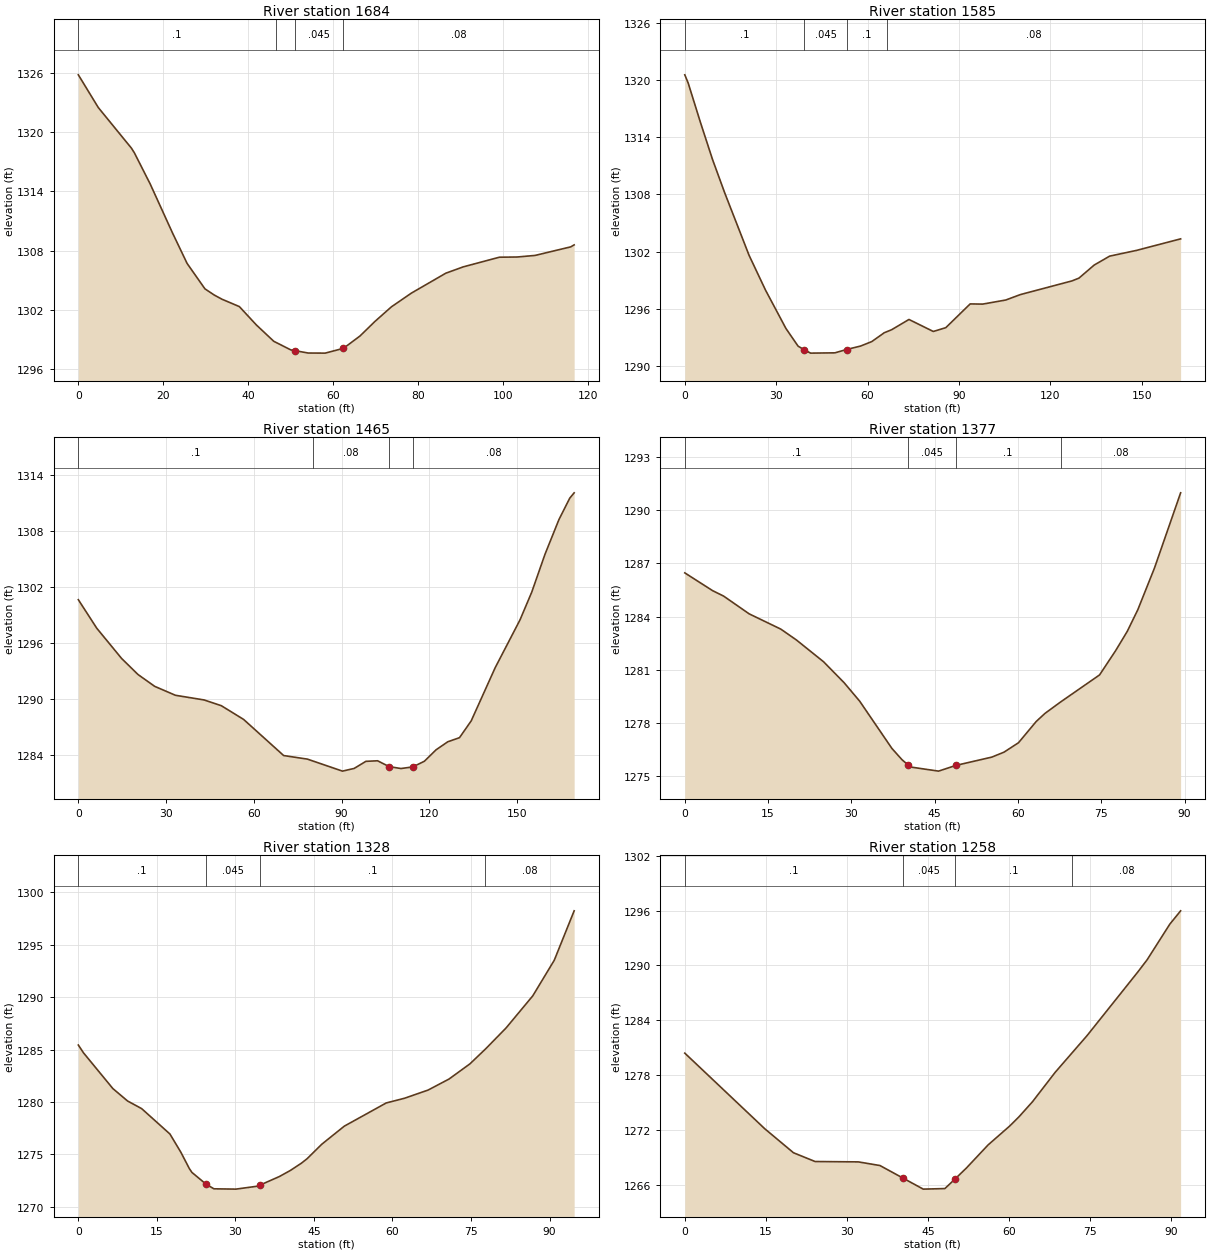
Type RM Length L Ch R = 1 ,1684    ,103,99.3,96.5
XS GIS Cut Line= 4
 2151210.0925293648049.7421775012151199.34901844648073.977539207
2151188.85535667648136.4398116452151197.35022572  648161.9244188
#Sta/Elev= 29
       0 1325.83     4.7 1322.51    12.5 1318.39    13.2 1317.91    16.9 1314.77
    22.2 1309.76    25.6  1306.7    29.8 1304.12      32 1303.49    33.8 1303.07
    37.9 1302.32    41.9 1300.46      46  1298.8      50 1297.93    50.9 1297.86
    54.1 1297.61    58.1  1297.6    62.41298.086    66.3 1299.34    69.8 1300.81
    73.7  1302.3    78.4 1303.69    86.5 1305.71    90.6 1306.35    99.1 1307.33
   103.3 1307.35   107.5 1307.51   115.9 1308.38   116.7 1308.58
#Mann= 4 ,-1,0
       0      .1       0   46.51     .08       0    50.9    .045       0
    62.4     .08       0
Bank Sta=50.9,62.4
XS Rating Curve= 0 ,0
Exp/Cntr(USF)=0,0
Exp/Cntr=0.3,0.1

Type RM Length L Ch R = 1 ,1585    ,119.4,119.7,120.9
XS GIS Cut Line= 5
2151105.70210661 648028.054697682151104.45286117648054.538701194
2151113.69727749648125.2459935942151130.18731741648135.739655363
2151158.17041546648171.468075198
#Sta/Elev= 30
       0 1320.53     1.1 1319.68     5.1 1315.58     9.1 1311.66    13.1 1308.16
    21.1 1301.61    26.5 1297.96    33.2 1293.94    37.2 1292.08    39.3 1291.69
    41.3 1291.35    49.3 1291.38    53.1 1291.73    57.7 1292.09    61.4 1292.56
    65.5 1293.49    67.9  1293.8    73.6 1294.88    81.6 1293.62    85.7 1294.02
    93.7 1296.51    97.8 1296.49   105.4 1296.92   110.2 1297.49   127.1 1298.92
   129.4 1299.21   134.4 1300.58   139.5 1301.52   148.3 1302.12   162.8 1303.33
#Mann= 4 ,-1,0
       0      .1       0    39.3    .045       0    53.1      .1       0
   66.51     .08       0
Bank Sta=39.3,53.1
XS Rating Curve= 0 ,0
Exp/Cntr(USF)=0,0
Exp/Cntr=0.3,0.1

Type RM Length L Ch R = 1 ,1465    ,81.9,88.3,92
XS GIS Cut Line= 5
2151052.64169829648034.6831941582151018.91207117648068.662670364
 2151008.4184094648075.1587466982151005.17037123 648154.36090815
2150994.92655855648182.593855292
#Sta/Elev= 30
       0 1300.65     6.3 1297.59    14.8 1294.34    20.4 1292.62    26.1 1291.35
    33.2 1290.39      43 1289.89    48.9 1289.27    56.5  1287.8    70.2 1283.92
    78.3 1283.54    90.3 1282.25    94.3 1282.54    98.3  1283.3   102.3 1283.36
   106.3 1282.73   110.3 1282.53   114.3  1282.7   118.3 1283.31   122.3 1284.54
   126.3  1285.4   130.3 1285.84   134.3 1287.64   142.5 1293.35     151 1298.49
     155 1301.46   159.5  1305.5   164.3 1309.25     168 1311.55   169.5 1312.12
#Mann= 4 ,-1,0
       0      .1       0   80.22     .08       0   106.3    .045       0
   114.3     .08       0
Bank Sta=106.3,114.3
XS Rating Curve= 0 ,0
Exp/Cntr(USF)=0,0
Exp/Cntr=0.3,0.1

Type RM Length L Ch R = 1 ,1377    ,51.6,49.3,45.6
XS GIS Cut Line= 4
2150980.80213882648037.4092290312150963.13456014648057.262487551
2150940.36706183   648091.5048052150927.61726278648108.990243697
#Sta/Elev= 27
       0 1286.46       5 1285.46       7 1285.15    11.6 1284.15    17.3 1283.29
    20.1 1282.68      25 1281.45    28.7 1280.27    31.5 1279.23    37.3 1276.57
    39.1 1275.94    40.2 1275.64    40.9 1275.51    45.7 1275.29    48.8 1275.61
    55.3 1276.08    57.5 1276.36    60.1 1276.89    63.3 1278.09    64.9 1278.55
    67.7 1279.19    74.7 1280.71    77.6 1282.08    79.7 1283.17    81.6 1284.39
    84.6 1286.74    89.3 1290.97
#Mann= 4 ,-1,0
       0      .1       0    40.2    .045       0    48.8      .1       0
    67.7     .08       0
Bank Sta=40.2,48.8
XS Rating Curve= 0 ,0
Exp/Cntr(USF)=0,0
Exp/Cntr=0.3,0.1

Type RM Length L Ch R = 1 ,1328    ,71.3,69.6,64.7
XS GIS Cut Line= 5
2150928.76939542  648020.4609789 2150916.9302963648032.664357991
2150908.00543697648062.3531757792150907.45901701648082.024294313
2150906.54831708648108.981012305
#Sta/Elev= 30
       0 1285.43       1 1284.68     6.6 1281.28     9.4  1280.1    12.1 1279.37
    17.5 1276.95    19.6  1275.2    21.2 1273.66    21.7 1273.29    24.4 1272.17
    25.9 1271.73    30.1  1271.7    34.2 1271.98    34.71272.085    38.4  1272.9
    40.5 1273.48    42.6 1274.17    43.7  1274.6    46.5 1275.98    50.8  1277.7
    58.8 1279.91    62.3 1280.36    66.8 1281.14    70.8 1282.19    74.8 1283.64
    77.8 1285.07    81.7 1287.06    86.8 1290.12    90.9 1293.51    94.7 1298.22
#Mann= 4 ,-1,0
       0      .1       0    24.4    .045       0    34.7      .1       0
   77.68     .08       0
Bank Sta=24.4,34.7
XS Rating Curve= 0 ,0
Exp/Cntr(USF)=0,0
Exp/Cntr=0.3,0.1

Type RM Length L Ch R = 1 ,1258    ,53.9,53.5,51.8
XS GIS Cut Line= 4
2150855.55699435648021.0845192882150854.16894386648052.732070656
2150854.44655395648082.7139614272150864.44051754648111.030191598
#Sta/Elev= 21
       0  1280.4    14.8 1272.12    20.1  1269.5    24.1 1268.54    32.1  1268.5
    36.1  1268.1    40.41266.713    44.1 1265.52    48.1 1265.58      50 1266.64
    52.1 1267.84    56.1 1270.36    60.1 1272.43    61.8 1273.43    64.3 1275.08
    68.5  1278.3    74.4 1282.32    83.8 1289.29    85.5 1290.61    89.7 1294.51
    91.7 1295.97
#Mann= 4 ,-1,0
       0      .1       0    40.4    .045       0      50      .1       0
   71.66     .08       0
Bank Sta=40.4,50
XS Rating Curve= 0 ,0
Exp/Cntr(USF)=0,0
Exp/Cntr=0.3,0.1

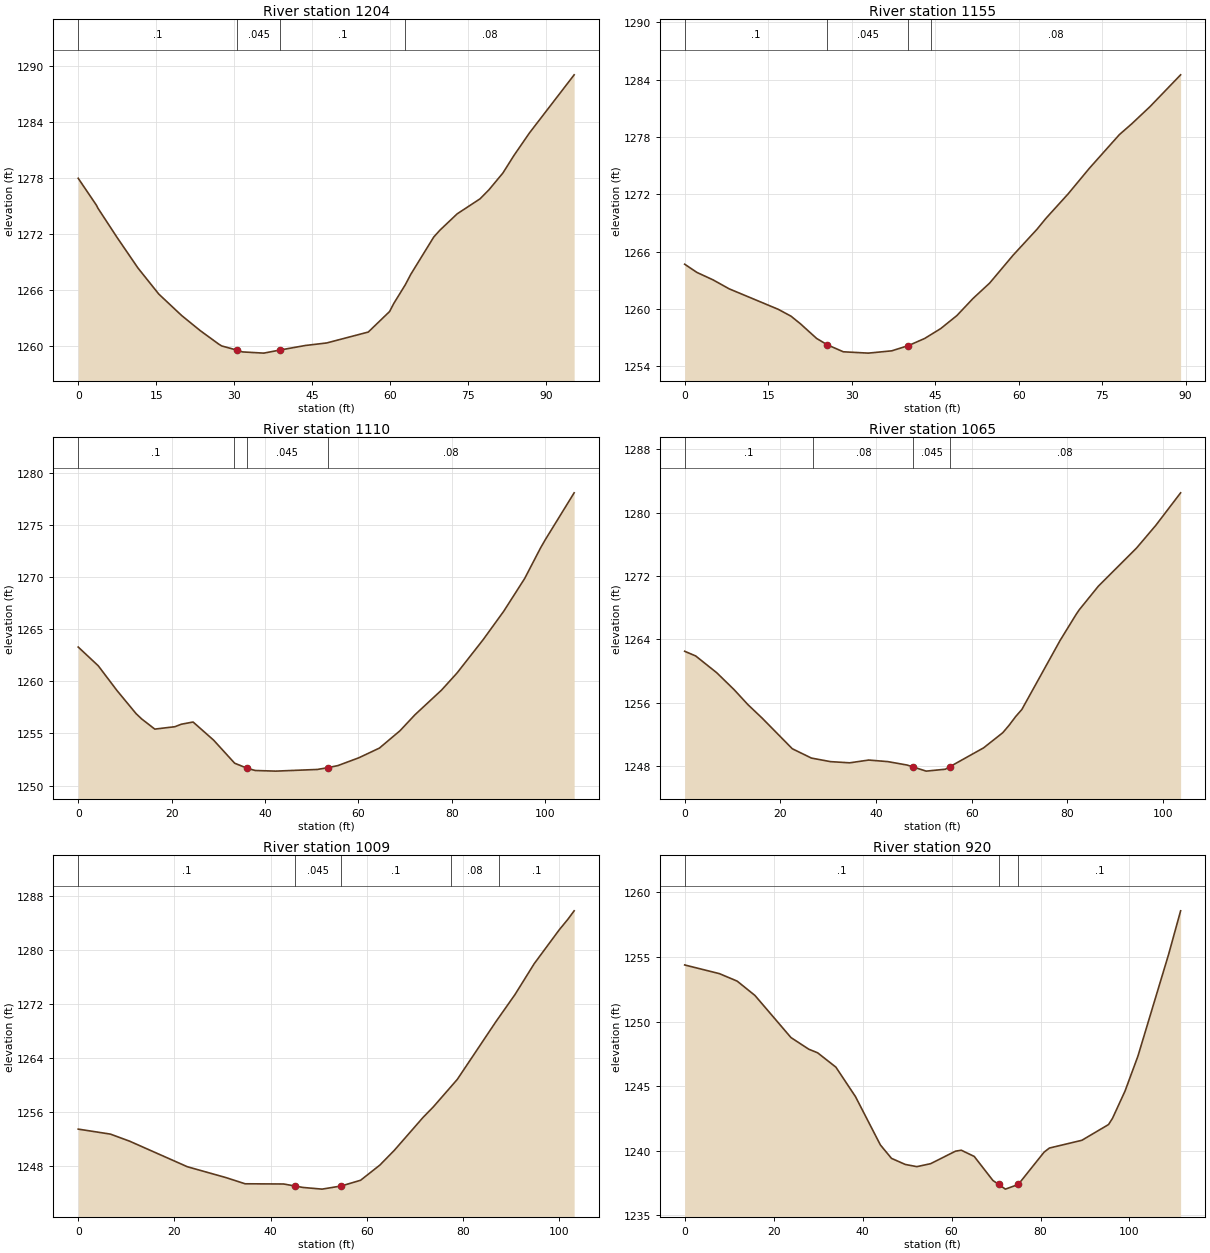
Type RM Length L Ch R = 1 ,1204    ,51.4,49.7,44.4
XS GIS Cut Line= 4
2150800.03497441648029.6904323792150799.20214411648044.681377764
 2150805.3095663648092.1527048172150819.19007129648121.579375388
#Sta/Elev= 30
       0 1277.96     3.5 1275.08     3.8 1274.75     7.5  1271.6    11.5 1268.34
    15.5 1265.55    19.9 1263.25    23.5 1261.62      27  1260.2    27.6 1259.99
    30.6 1259.53    31.6 1259.35    35.7 1259.22    38.81259.551    43.7 1260.04
    47.8 1260.31    55.8 1261.48    59.9 1263.68    60.7 1264.54    62.9 1266.53
      64 1267.69    68.4 1271.67    69.6 1272.41    72.9 1274.15    77.3 1275.76
      79 1276.72    81.7 1278.53    83.8 1280.39    86.8 1282.82    95.4 1289.05
#Mann= 4 ,-1,0
       0      .1       0    30.6    .045       0    38.8      .1       0
   62.88     .08       0
Bank Sta=30.6,38.8
XS Rating Curve= 0 ,0
Exp/Cntr(USF)=0,0
Exp/Cntr=0.3,0.1

Type RM Length L Ch R = 1 ,1155    ,43.7,45.2,45.9
XS GIS Cut Line= 4
2150745.59804971648060.7637371652150752.88364917 648073.10878069
2150773.93093649648108.7272669252150796.59724591648133.214976211
#Sta/Elev= 27
       0 1264.67     2.2 1263.81     5.1 1263.03       8 1262.09    16.8 1259.95
    19.1 1259.23    20.8 1258.43    23.7  1256.9    25.6 1256.24    28.5  1255.5
      33 1255.36    37.2  1255.6    40.2 1256.15    43.1 1256.89      46 1257.93
    48.9 1259.29    51.8 1261.08    54.8  1262.7      59 1265.61    63.3 1268.33
    64.9 1269.47    68.9 1272.04    72.7 1274.71    78.1 1278.24    80.3 1279.36
    83.6 1281.17    89.1  1284.5
#Mann= 4 ,-1,0
       0      .1       0    25.6    .045       0    40.2      .1       0
   44.33     .08       0
Bank Sta=25.6,40.2
XS Rating Curve= 0 ,0
Exp/Cntr(USF)=0,0
Exp/Cntr=0.3,0.1

Type RM Length L Ch R = 1 ,1110    ,39.9,44.9,48.6
XS GIS Cut Line= 4
2150708.89976615648064.9523812212150712.36042589648088.084159498
 2150735.1279242648135.9869759292150748.24200322648162.761553934
#Sta/Elev= 29
       0 1263.28     4.3 1261.48     8.3 1259.11    12.4 1256.89    13.6 1256.38
    16.4 1255.41    20.7 1255.64    22.1 1255.88    24.6 1256.09      29 1254.35
    33.5 1252.14    36.1 1251.67    37.9 1251.44    42.3 1251.38    51.2 1251.54
    53.51251.714    55.6 1251.91    60.1 1252.66    64.5 1253.59    68.9 1255.25
    72.1 1256.78    77.8 1259.15    81.1 1260.78    86.7 1263.98    91.1  1266.7
    95.6 1269.85      99 1272.78     100 1273.56   106.2 1278.07
#Mann= 4 ,-1,0
       0      .1       0   33.39     .08       0    36.1    .045       0
    53.5     .08       0
Bank Sta=36.1,53.5
XS Rating Curve= 0 ,0
Exp/Cntr(USF)=0,0
Exp/Cntr=0.3,0.1

Type RM Length L Ch R = 1 ,1065    ,55.4,55.3,55
XS GIS Cut Line= 4
2150684.87020254648070.8860049842150682.37171164648087.625893997
2150681.37231528648142.5926937432150679.37352256648174.323528141
#Sta/Elev= 29
       0 1262.48     2.3 1261.89     6.7 1259.77    10.4 1257.59    13.2 1255.75
    16.2 1254.03    22.5 1250.16    26.5 1248.98    30.5 1248.53    34.5 1248.38
    38.5 1248.73    42.5 1248.53    46.5  1248.1    47.8 1247.85    50.5 1247.33
    54.5 1247.57    55.41247.874    62.5 1250.27    66.5 1252.18    67.8  1253.1
    69.2 1254.22    70.5 1255.12    78.5 1263.85    81.9 1267.19    82.5 1267.72
    86.5 1270.71    94.5 1275.54    98.5 1278.39   103.7 1282.51
#Mann= 4 ,-1,0
       0      .1       0   26.93     .08       0    47.8    .045       0
    55.4     .08       0
Bank Sta=47.8,55.4
XS Rating Curve= 0 ,0
Exp/Cntr(USF)=0,0
Exp/Cntr=0.3,0.1

Type RM Length L Ch R = 1 ,1009    ,79.9,89.8,94.5
XS GIS Cut Line= 3
 2150626.0381115648074.4426285742150627.27193417648151.865000831
2150625.11274451648177.466821139
#Sta/Elev= 23
       0 1253.53     6.7 1252.79    10.7 1251.74    22.7 1247.96    30.7 1246.36
    34.7 1245.44    42.7 1245.41      451245.117    46.7  1244.9    50.7 1244.65
    54.7 1245.12    58.7 1245.96    62.7  1248.2    65.7 1250.38    71.7 1255.27
    73.8  1256.8    78.8 1260.88    86.8 1269.39    90.8 1273.44    94.8 1278.01
     100 1283.02   101.8 1284.58   103.1 1285.83
#Mann= 5 ,-1,0
       0      .1       0      45    .045       0    54.7      .1       0
   77.43     .08       0   87.43      .1       0
Bank Sta=45,54.7
XS Rating Curve= 0 ,0
Exp/Cntr(USF)=0,0
Exp/Cntr=0.3,0.1

Type RM Length L Ch R = 1 ,920     ,63,61.7,58.7
XS GIS Cut Line= 4
2150619.86899818648061.4874905872150590.25725421 648065.49741425
2150551.39184025648103.745916879 2150533.5014116648124.103990859
#Sta/Elev= 30
       0 1254.39     7.8 1253.72    11.8 1253.14    15.8 1252.03    23.9 1248.77
    27.9 1247.87    29.9 1247.59      34 1246.48    38.4  1244.2      44 1240.46
    46.5 1239.42    49.6 1238.95    52.2 1238.78    55.3 1239.01    60.9 1239.98
    62.2 1240.05    65.1 1239.57    69.3 1237.71    70.61237.404    72.1 1237.04
      75  1237.4    80.8  1239.9      82 1240.22    89.3 1240.82    95.3 1242.04
    96.2 1242.53      99 1244.63   101.9 1247.33   108.8 1255.21   111.5 1258.58
#Mann= 3 ,-1,0
       0      .1       0    70.6    .045       0      75      .1       0
Bank Sta=70.6,75
XS Rating Curve= 0 ,0
Exp/Cntr(USF)=0,0
Exp/Cntr=0.3,0.1

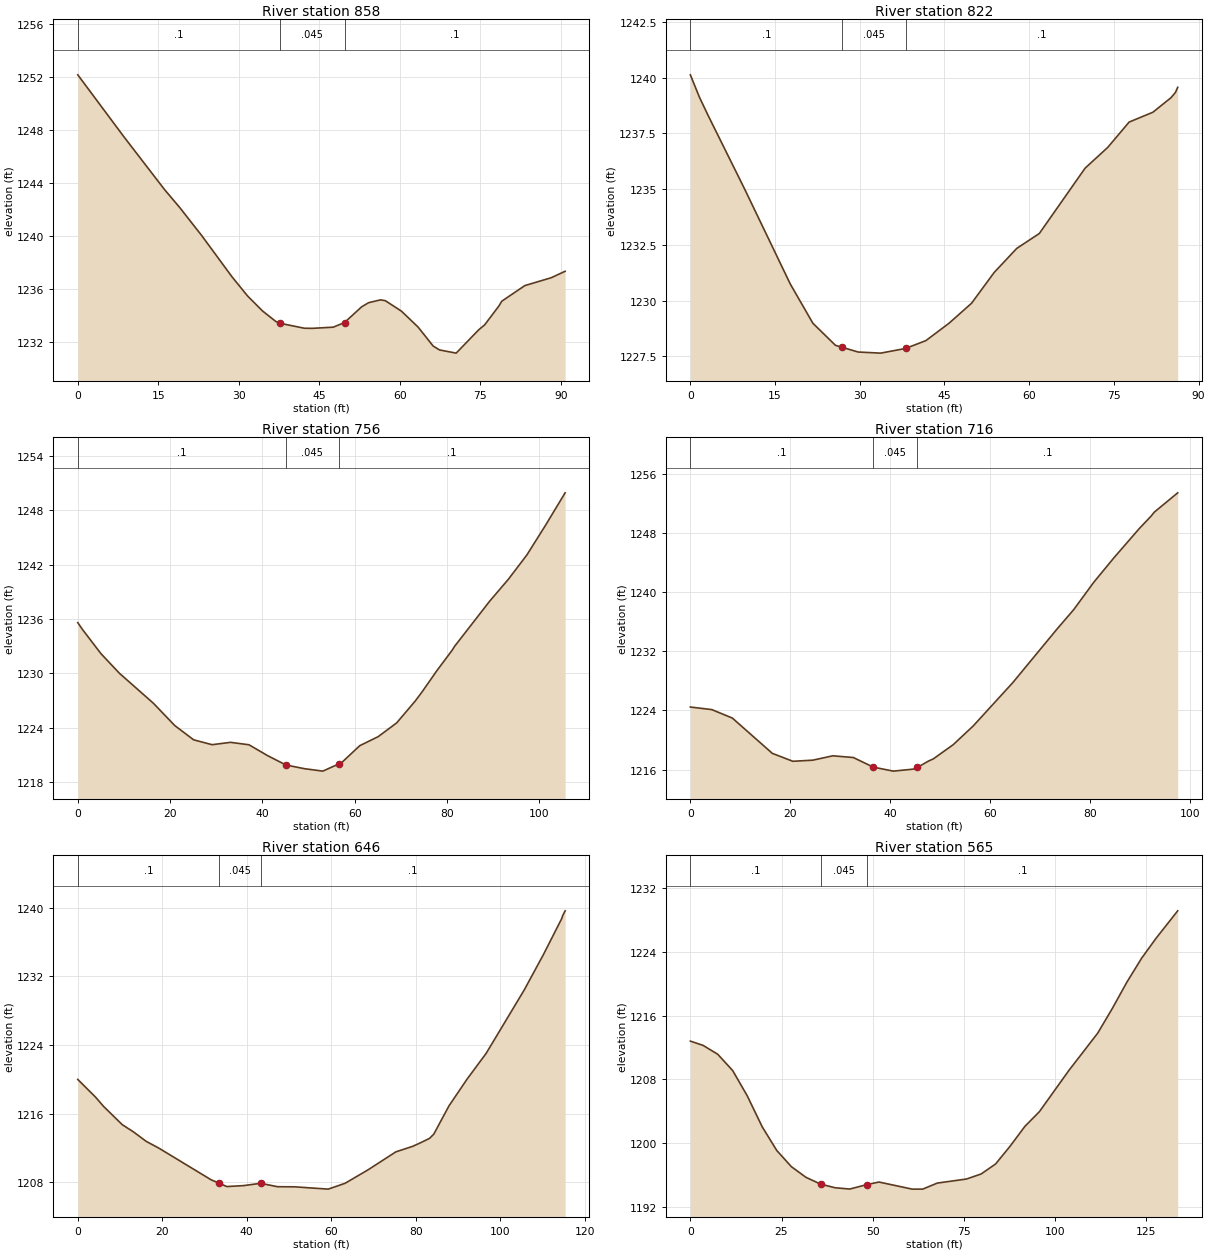
Type RM Length L Ch R = 1 ,858     ,42.8,36.1,29
XS GIS Cut Line= 4
2150562.68818908648007.7107340012150550.19573459648026.449415732
2150528.70871287648050.684777438 2150515.7165602648084.164555465
#Sta/Elev= 30
       0 1252.18     8.6  1247.5    16.2  1243.5      19 1242.16    23.1 1240.04
    28.7 1236.95    31.6  1235.5    34.4 1234.36    36.9 1233.56    37.6 1233.43
    42.2 1233.05    43.7 1233.04    47.6 1233.13    49.7 1233.48    52.9 1234.67
    54.2 1234.98    56.4 1235.19    57.3 1235.13    60.3 1234.34    63.4 1233.14
    66.2 1231.71    67.4 1231.41    70.5 1231.17    74.7 1232.93    75.8  1233.3
    78.5 1234.75      79 1235.09    83.3 1236.27    88.2 1236.86    90.8 1237.35
#Mann= 3 ,-1,0
       0      .1       0    37.6    .045       0    49.7      .1       0
Bank Sta=37.6,49.7
XS Rating Curve= 0 ,0
Exp/Cntr(USF)=0,0
Exp/Cntr=0.3,0.1

Type RM Length L Ch R = 1 ,822     ,62.5,65.4,62.6
XS GIS Cut Line= 2
2150506.90350732647995.5952746232150499.22429864648081.602411742
#Sta/Elev= 24
       0 1240.13     1.6 1239.13     3.1 1238.33     9.6 1235.01    17.7 1230.74
    21.7 1228.98    25.7 1227.99    26.9  1227.9    29.7 1227.69    33.7 1227.64
    38.11227.849    41.7  1228.2    45.8 1228.98    49.8 1229.88    53.8 1231.26
    57.8 1232.34    61.8 1233.01    69.9 1235.94    73.9 1236.87    77.7 1238.01
    81.9 1238.45    85.1  1239.1    85.9 1239.34    86.3 1239.57
#Mann= 3 ,-1,0
       0      .1       0    26.9    .045       0    38.1      .1       0
Bank Sta=26.9,38.1
XS Rating Curve= 0 ,0
Exp/Cntr(USF)=0,0
Exp/Cntr=0.3,0.1

Type RM Length L Ch R = 1 ,756     ,41.4,40,40.4
XS GIS Cut Line= 4
2150450.25609869647992.2200904362150447.25790961648025.200170283
2150447.75760779648066.6751191822150451.75519323648097.406557222
#Sta/Elev= 29
       0  1235.6       1 1234.86       5 1232.19       9 1230.02    16.4 1226.69
      21 1224.24    25.1 1222.66    29.1 1222.12    33.1 1222.38    37.1 1222.11
    41.1 1220.92    45.1 1219.88    49.1 1219.47    53.1  1219.2    56.5 1219.98
    57.1  1220.1    61.1 1222.01    65.1 1223.01    69.1 1224.53    73.1 1226.93
    74.6 1227.95    77.8 1230.29    81.2 1232.61    81.6 1232.95    89.2 1237.94
    93.3 1240.39    97.3 1243.07   101.3 1246.31   105.6 1249.94
#Mann= 3 ,-1,0
       0      .1       0    45.1    .045       0    56.5      .1       0
Bank Sta=45.1,56.5
XS Rating Curve= 0 ,0
Exp/Cntr(USF)=0,0
Exp/Cntr=0.3,0.1

Type RM Length L Ch R = 1 ,716     ,69.6,70.1,70.3
XS GIS Cut Line= 4
2150413.95546557648012.902367572 2150409.9455419 648041.89720021
2150408.09480791 648081.687981172150404.08488424648109.757446809
#Sta/Elev= 25
       0 1224.45     4.3  1224.1     8.4 1222.96    16.4 1218.19    20.5 1217.12
    24.5 1217.27    28.5 1217.86    32.6 1217.63    36.6 1216.33    40.6 1215.79
    44.6 1216.06    45.41216.284    47.7 1217.17    48.6 1217.44    52.6 1219.37
    56.6  1221.9    64.5 1227.74    73.3 1234.94    76.7 1237.61    80.7  1241.3
    84.8 1244.66    89.8 1248.55    92.2 1250.26    92.8 1250.77    97.5 1253.39
#Mann= 3 ,-1,0
       0      .1       0    36.6    .045       0    45.4      .1       0
Bank Sta=36.6,45.4
XS Rating Curve= 0 ,0
Exp/Cntr(USF)=0,0
Exp/Cntr=0.3,0.1

Type RM Length L Ch R = 1 ,646     ,80.6,81.2,80
XS GIS Cut Line= 4
2150352.18396999647999.6312852482150344.30121407648016.424982639
 2150342.3270978648082.1089031482150356.55375859 648109.79108556
#Sta/Elev= 30
       0 1219.99     4.2 1217.93     6.1 1216.85    10.5 1214.73    13.2 1213.87
    16.2 1212.77    19.2 1211.98    31.6 1208.28    33.51207.888    35.3  1207.5
    39.3 1207.61    43.3 1207.88    47.3 1207.48    51.3 1207.47    59.3  1207.2
    63.3 1207.88    68.7 1209.44    75.3 1211.54    79.3 1212.19    81.1 1212.59
    83.3 1213.12    84.3 1213.61    87.9 1216.91    92.2 1220.04    96.7 1223.03
   105.7 1230.41   110.2 1234.49   114.6 1238.75   114.8 1239.06   115.4 1239.65
#Mann= 3 ,-1,0
       0      .1       0    33.5    .045       0    43.3      .1       0
Bank Sta=33.5,43.3
XS Rating Curve= 0 ,0
Exp/Cntr(USF)=0,0
Exp/Cntr=0.3,0.1

Type RM Length L Ch R = 1 ,565     ,87,89.5,89
XS GIS Cut Line= 4
2150267.17073243648005.7312842392150264.08617577648025.266809775
 2150266.4852754648107.8643826552150265.45708984648139.052677809
#Sta/Elev= 30
       0 1212.81     3.5 1212.27     7.5 1211.16    11.6 1209.11    15.6 1205.93
    19.7 1202.04    23.7 1199.06    27.7 1197.03    31.7 1195.69    35.7 1194.84
    39.7 1194.38    43.7 1194.22    48.4 1194.78    51.7  1195.1    60.8 1194.21
    63.7 1194.21    67.7 1194.97    75.7 1195.48    79.7 1196.11    83.7 1197.38
    87.7 1199.63    91.7 1202.09    95.7 1203.95   103.7 1209.08   111.7 1213.83
   115.7 1216.93   119.7 1220.24   123.7 1223.22   127.7 1225.75   133.6 1229.18
#Mann= 3 ,-1,0
       0      .1       0    35.7    .045       0    48.4      .1       0
Bank Sta=35.7,48.4
XS Rating Curve= 0 ,0
Exp/Cntr(USF)=0,0
Exp/Cntr=0.3,0.1

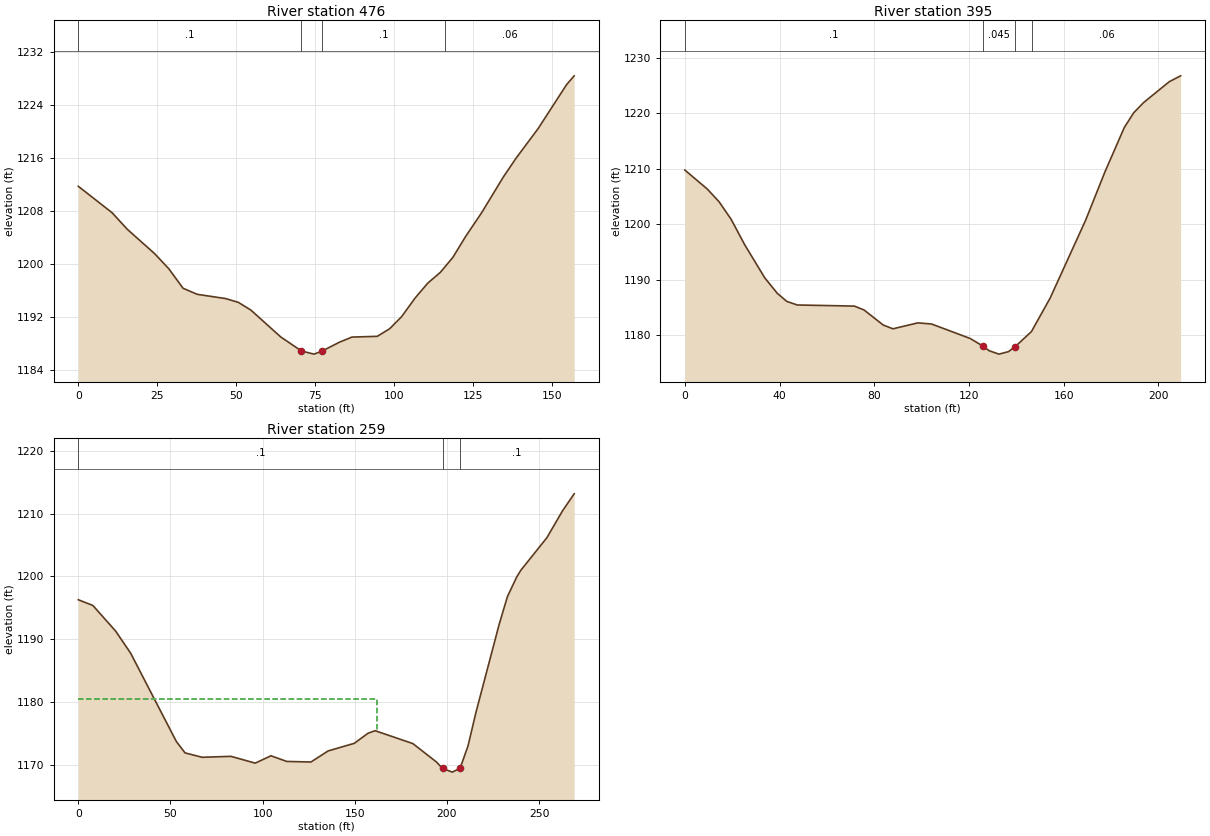
Type RM Length L Ch R = 1 ,476     ,75.9,80.3,76.3
XS GIS Cut Line= 4
2150215.55282083647987.6617036272150194.39673946648028.563460941
2150191.10579347 648101.904543022150191.10579347648139.515354342
#Sta/Elev= 30
       0 1211.71    10.7 1207.73    15.5 1205.24    24.2 1201.55    28.7 1199.27
    33.2 1196.34    37.7 1195.43    46.7 1194.79    50.7 1194.22    54.7 1193.05
    64.1 1189.02    70.7 1186.89    74.7 1186.42    77.31186.895    82.7 1188.21
    86.7 1188.99    94.7  1189.1    98.6 1190.23   102.4 1192.05   106.7 1194.87
   110.7 1197.11   114.7 1198.74   118.7 1201.02   122.7 1204.14   127.8 1207.74
   134.7 1213.14   138.7 1215.95   145.7 1220.42   154.7 1227.03   157.1 1228.36
#Mann= 4 ,-1,0
       0      .1       0    70.7    .045       0    77.3      .1       0
  116.05     .06       0
Bank Sta=70.7,77.3
XS Rating Curve= 0 ,0
Exp/Cntr(USF)=0,0
Exp/Cntr=0.3,0.1

Type RM Length L Ch R = 1 ,395     ,217.5,136.1,208.2
XS GIS Cut Line= 3
2150155.97888016647953.5723140532150133.87070772647982.833130511
 2150102.0089298648152.545865969
#Sta/Elev= 30
       0 1209.79     9.5 1206.36    14.5 1204.05    19.6 1200.87    25.3  1196.3
    33.8 1190.31    39.1 1187.52    43.1 1186.07    47.5 1185.43    71.6 1185.23
    75.7 1184.53    83.8 1181.81    87.9 1181.13    98.4  1182.2   104.2    1182
   120.5 1179.39   125.8 1178.04   128.6 1177.16   132.7 1176.56   136.7 1177.01
   139.5  1177.9   146.4 1180.63   154.3 1186.68   169.3 1200.75   177.4 1209.41
   185.6 1217.45   189.6 1220.13   193.7 1221.94   204.6 1225.73   209.4 1226.79
#Mann= 4 ,-1,0
       0      .1       0   125.8    .045       0   139.5      .1       0
  146.67     .06       0
Bank Sta=125.8,139.5
XS Rating Curve= 0 ,0
Exp/Cntr(USF)=0,0
Exp/Cntr=0.3,0.1

Type RM Length L Ch R = 1 ,259     ,168.4,168.4,168.4
XS GIS Cut Line= 3
  2149965.458453647905.4545269882149955.70484751 647950.97135259
2150034.38393176648159.048269626
#Sta/Elev= 30
       0 1196.29     7.9 1195.38    20.2 1191.32    28.4 1187.78    53.2 1173.73
    57.9 1171.93    67.2 1171.23    82.8 1171.38      96  1170.3   104.5 1171.47
   113.1 1170.57   126.2 1170.48   135.5 1172.24   149.7 1173.45   157.2 1175.06
     161 1175.46   181.5 1173.41   194.3 1170.48   197.6 1169.45   202.9 1168.87
   207.1 1169.48   211.4 1173.02   215.7 1178.35   228.3 1192.36   232.8 1196.79
   237.9 1199.95   240.1 1200.99   254.2 1206.16   262.7 1210.44     269 1213.14
#Mann= 3 ,-1,0
       0      .1       0   197.6    .045       0   207.1      .1       0
#XS Ineff= 2 , 0
          161.92 1180.44
Permanent Ineff=
       F       F
Bank Sta=197.6,207.1
XS Rating Curve= 0 ,0
Exp/Cntr(USF)=0,0
Exp/Cntr=0.3,0.1