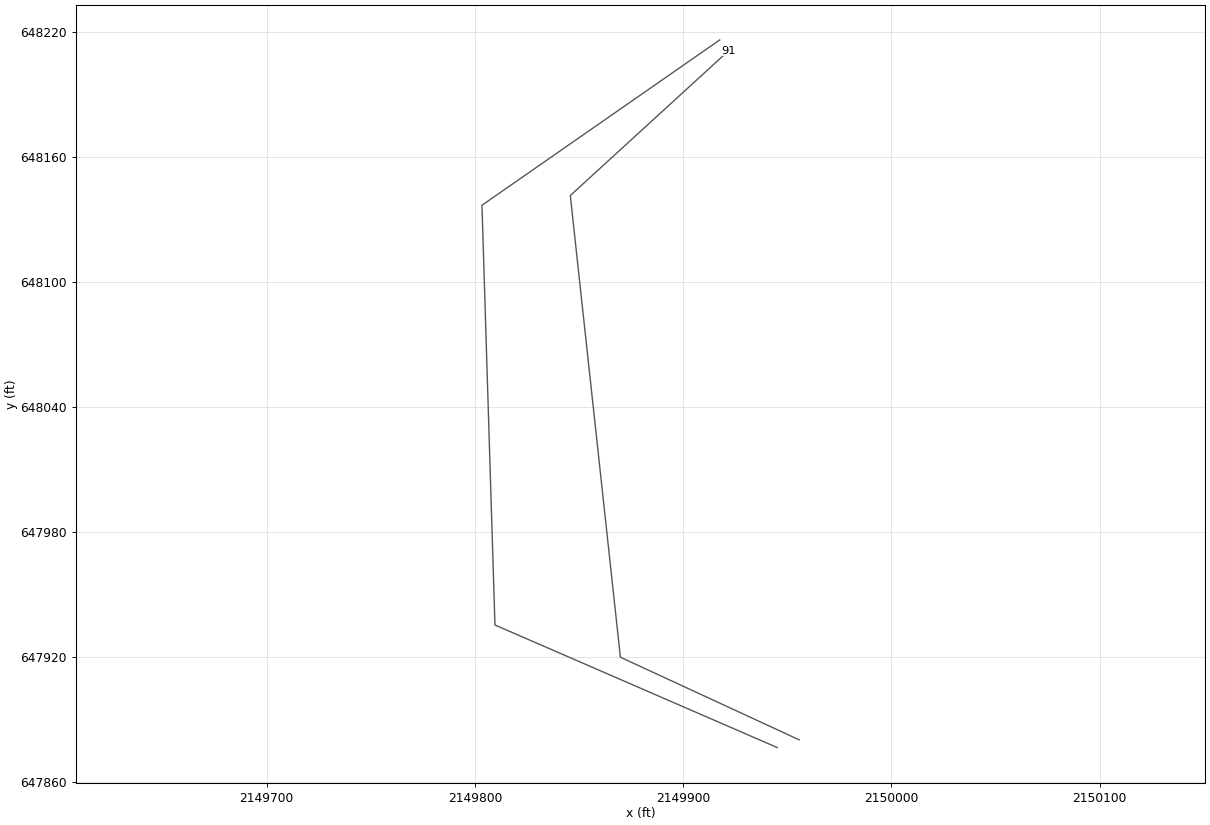
HEC-RAS study LYNNCMPRN.prj: LYNNCMPRN

--- LYNNCMPRN.g01 (geometry) --- (continued)

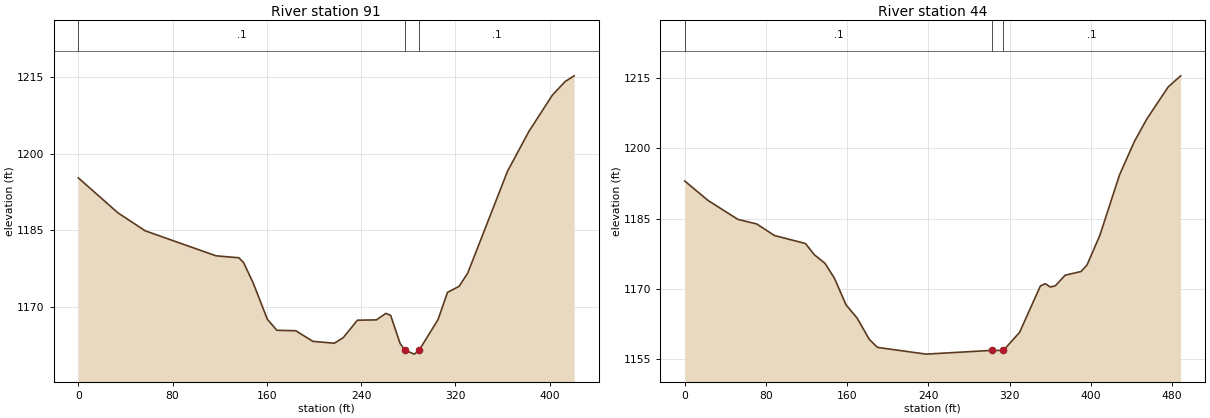
Type RM Length L Ch R = 1 ,91      ,47.1,47.1,47.1
XS GIS Cut Line= 4
2149955.70484751647880.0951527242149869.87311923647919.759815034
 2149845.8142257648141.4917797512149921.89234849648211.067498885
#Sta/Elev= 30
       0 1195.24    33.6 1188.41    56.8 1184.89   116.8 1180.01   136.2 1179.63
   140.2 1178.69   148.3 1174.74   160.4 1167.61   168.4 1165.46   184.5 1165.37
     199  1163.3   217.2 1162.93   224.7    1164   236.8 1167.43   252.9 1167.49
   260.9 1168.76     265 1168.37     273 1162.89     277 1161.58   285.1  1160.8
   289.1 1161.54   305.2 1167.55   313.2 1172.87   323.1 1174.05   330.4 1176.65
   364.1 1196.51   382.3 1204.32   402.1 1211.38   412.9 1214.04420.6823 1215.18
#Mann= 3 ,-1,0
       0      .1       0     277    .045       0   289.1      .1       0
Bank Sta=277,289.1
XS Rating Curve= 0 ,0
Exp/Cntr(USF)=0,0
Exp/Cntr=0.3,0.1

Type RM Length L Ch R = 1 ,44      ,,,
XS GIS Cut Line= 4
 2149945.2083944647876.3645253282149809.63015628 647935.23402346
2149803.38642163 648136.817456462149917.55756952 648216.20208273
#Sta/Elev= 30
       0 1193.05    22.9  1188.9    52.3 1184.86    70.9 1183.88    88.3 1181.42
   118.9  1179.7   127.6 1177.31   138.2 1175.46   147.4 1172.31   158.9  1166.6
   169.8 1163.78   181.8 1159.24   189.8 1157.52   237.8 1156.08   302.5 1156.88
   313.8 1156.86   329.8  1160.7   350.4 1170.65   355.3 1171.12   360.2 1170.41
   365.1 1170.68   374.8 1172.94   390.5 1173.73   396.3 1175.11   408.9 1181.41
   428.4 1194.39     443  1201.5   455.2 1206.29   476.2 1213.12488.5451 1215.52
#Mann= 3 ,-1,0
       0      .1       0   302.5    .045       0   313.8      .1       0
Bank Sta=302.5,313.8
XS Rating Curve= 0 ,0
Exp/Cntr(USF)=0,0
Exp/Cntr=0.3,0.1
LCMann Table=0

Chan Stop Cuts=-1
Use User Specified Reach Order=0
Composite Channel Slope=5